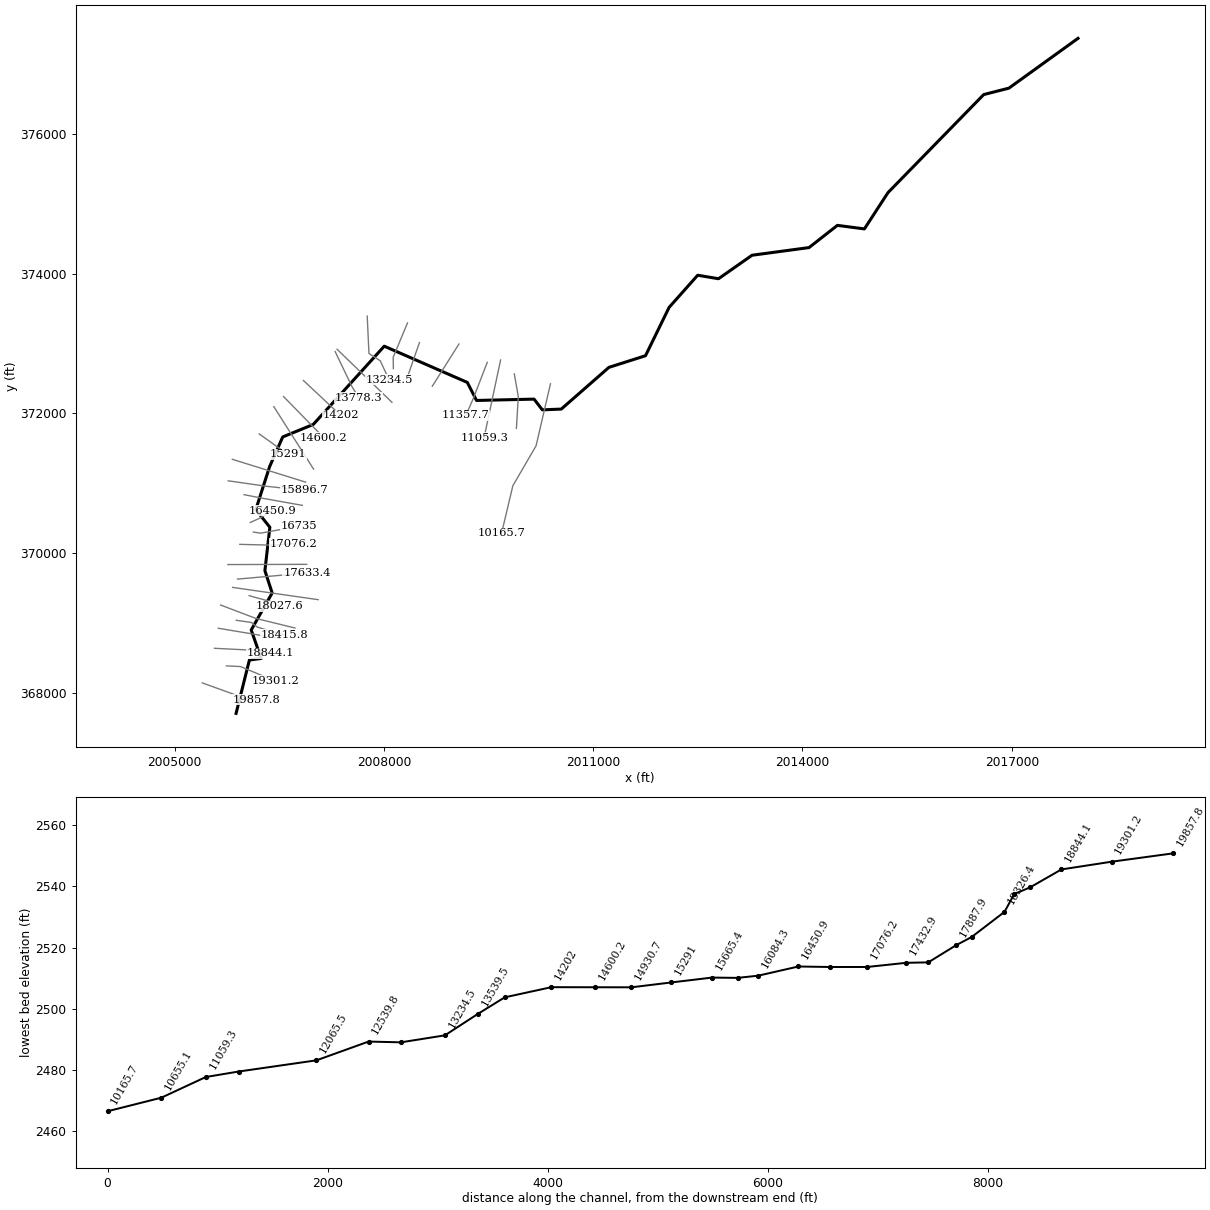
--- LaurelCrk5.prj (project) ---

Proj Title=LaurelCrk5
Current Plan=p01
Default Exp/Contr=0,0
English Units
Geom File=g01
Flow File=f01
Plan File=p01
BEGIN DESCRIPTION:
END DESCRIPTION:
DSS Export Rating Curves= 0
DSS Export Rating Curve Sorted= 0
DSS Export Volume Flow Curves= 0
DXF OffsetX= 0
DXF OffsetY= 0
DXF ScaleX= 0
DXF ScaleY= 0

--- LaurelCrk5.p01 (plan) ---

Plan Title=Floodplain
Program Version=4.00
Geom File=g01
Flow File=f01
K Sum by GR=0
Std Step Tol=0.01
Critical Tol=0.01
Num of Std Step Trials=20
Max Error Tol=0.3
Flow Tol Ratio=0.001
Split Flow NTrial=30
Split Flow Tol=0.02
Split Flow Ratio=0.02
Log Output Level=0
Friction Slope Method=1
Unsteady Friction Slope Method=2
Unsteady Bridges Friction Slope Method=1
Global Log Level=0
CheckData=False
Run HTab=0
Run UNet=0
Run PostProcess=0
UNET Theta=0
UNET Theta Warmup=0
UNET ZTol=0
UNET ZSATol=0
UNET MxIter=0
UNET MaxInSteps=0
UNET DtIC=0
UNET DtMin=0
UNET MaxCRTS=0
UNET WFStab=0
UNET SFStab=0
UNET WFX=0
UNET SFX=0
UNET DSS MLevel=0
UNET DZMax Abort=0
UNET Convert EG Bridges=0
UNET Use Existing IB Tables=0
UNET Froude Limit=0
UNET Froude Power=0
Write IC File=0
Echo Input=False
Echo Output=False
Write Detailed=0

--- LaurelCrk5.f01 (steady flow) ---

Flow Title=NFF Regression Equation
Program Version=4.00
Number of Profiles=1
Profile Names=P100yr
River Rch & RM=LaurelCrk5,Main      ,19857.8
540.5761
River Rch & RM=LaurelCrk5,Main      ,16450.9
590.5582
River Rch & RM=LaurelCrk5,Main      ,12833.9
655.4587
River Rch & RM=LaurelCrk5,Main      ,12539.8
772.3794
River Rch & RM=LaurelCrk5,Main      ,10165.7
806.3964
River Rch & RM=LaurelCrk5,Main      ,9735.1
1518.821
River Rch & RM=LaurelCrk5,Main      ,7171.1
1616.156
River Rch & RM=LaurelCrk5,Main      ,278.8
1788.054
Boundary for River Rch & Prof#=LaurelCrk5,Main      ,1
Up Type=0
Dn Type=3
Dn Slope=0.016709

--- LaurelCrk5.g01 (geometry) ---

Geom Title=USGS 3m DEM
Program Version=4.10

River Reach=LaurelCrk5      ,Main
Reach XY= 30
     2005881.993       367704.28     2006072.965      368468.169
     2006241.368      368490.738     2006099.006      368898.724
     2006399.354      369428.238     2006295.187      369747.682
     2006365.955      370369.182     2006164.979      370622.682
     2006361.607      371234.804     2006550.395      371662.613
     2006987.895      371841.433     2008005.604      372962.382
     2009195.874      372443.682     2009328.488      372185.183
     2010152.826       372204.28     2010270.926      372051.002
     2010542.667      372061.505     2011225.743      372659.141
     2011750.048      372825.808      2012088.59      373518.516
     2012497.901        373978.3     2012796.389      373928.238
     2013277.231      374264.746     2014093.798      374374.419
     2014500.135      374692.486     2014887.201       374641.78
     2015225.902      375161.937     2016597.271      376565.391
     2016958.381      376657.405     2017949.064      377370.757

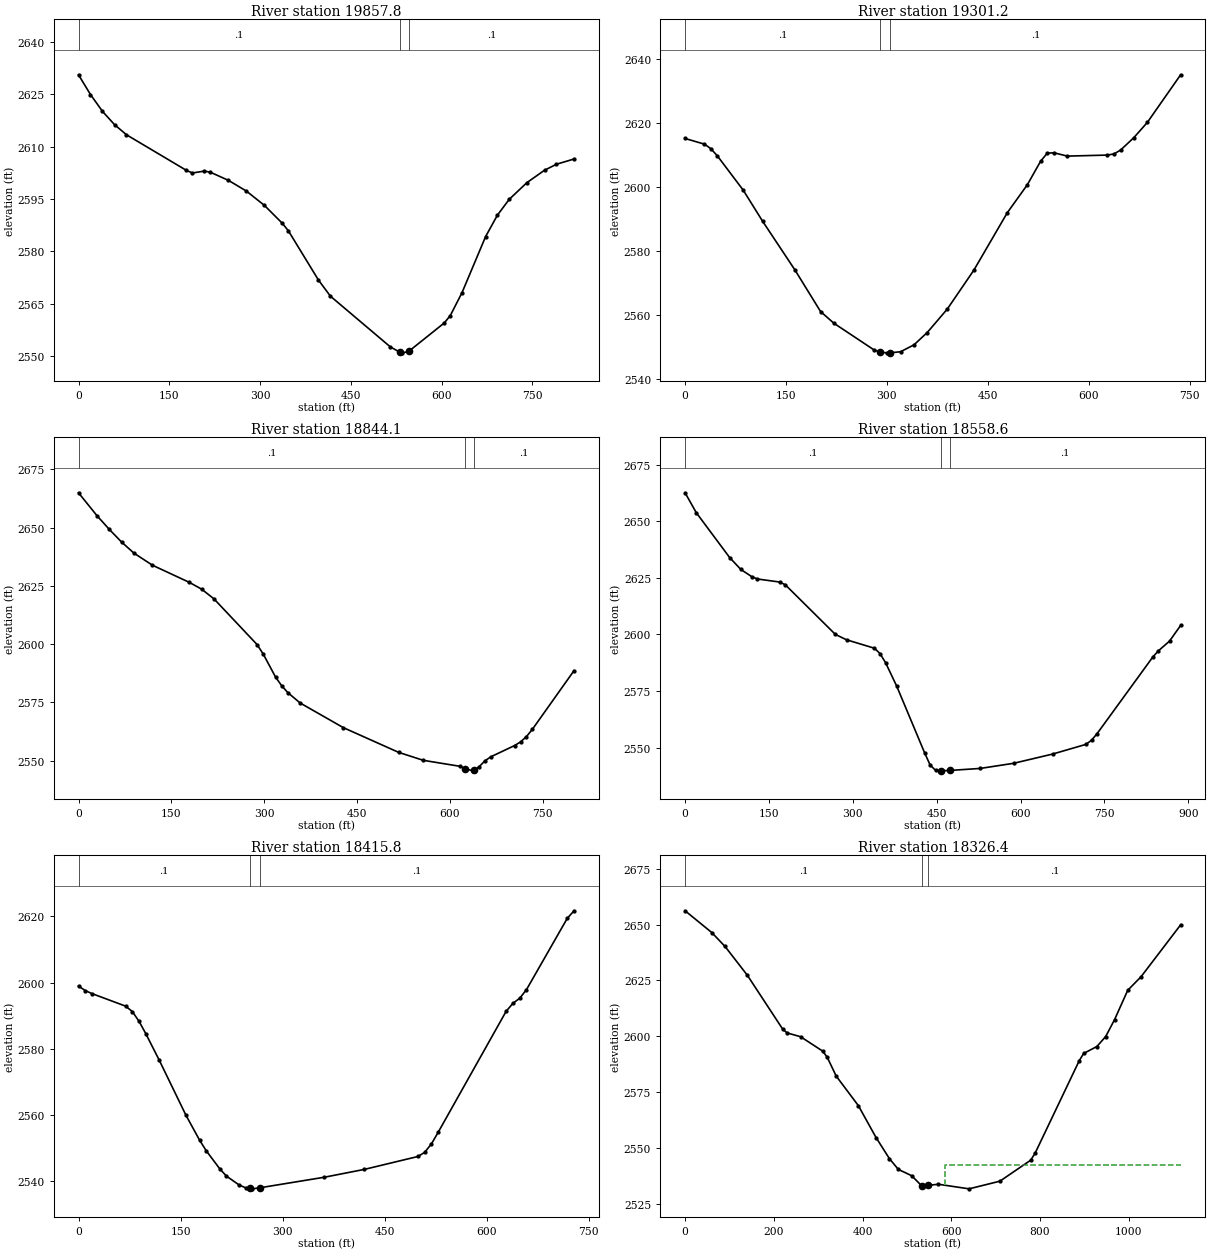
Type RM Length L Ch R = 1 ,19857.8 ,557.1,555.8,547.2
XS GIS Cut Line= 3
     2005398.787      368140.507     2005967.392      367935.246
     2006178.446      367898.001
#Sta/Elev= 30
       0 2630.65    19.8 2624.98    39.6 2620.15    59.5 2616.34    79.3 2613.43
   178.4  2603.2   188.3 2602.46   208.1 2603.01     218 2602.67   247.8 2600.34
   277.5 2597.26   307.2 2593.16     337 2587.98   346.9 2585.83   396.4 2571.76
   416.2 2567.11   515.3 2552.54   530.4 2551.08   535.2 2550.84   545.4 2551.23
   604.5 2559.44   614.3 2561.53   633.7 2568.12   672.7 2584.22   692.2 2590.37
   711.7  2594.9   740.9 2599.69   770.1 2603.26   789.6 2604.96   818.8 2606.48
#Mann= 3 , 0 , 0
       0      .1       0   530.4    .045       0   545.4      .1       0
Bank Sta=530.4,545.4
XS Rating Curve= 0 ,0
Exp/Cntr=0.3,0.1

Type RM Length L Ch R = 1 ,19301.2 ,433.2,456.5,465
XS GIS Cut Line= 3
     2005743.923      368384.667     2005945.045      368374.735
      2006439.16      368168.647
#Sta/Elev= 30
       0 2615.17    28.8  2613.4    38.4 2611.96    47.9 2609.75    86.3 2599.04
   115.1 2589.33     163 2574.14   201.4 2561.04   221.2 2557.38   280.7 2549.06
   289.6 2548.34   300.5 2548.12   304.6 2548.13   320.3 2548.46   340.2 2550.61
     360 2554.48   389.7 2561.79   429.4 2574.02     479 2591.95   508.7 2600.67
   528.5 2608.04   538.4 2610.58   548.4  2610.7   568.2 2609.66   627.7 2609.98
   637.6 2610.34   647.5 2611.56   667.3 2615.47   687.2  2620.2   736.7  2635.1
#Mann= 3 , 0 , 0
       0      .1       0   289.6    .045       0   304.6      .1       0
Bank Sta=289.6,304.6
XS Rating Curve= 0 ,0
Exp/Cntr=0.3,0.1

Type RM Length L Ch R = 1 ,18844.1 ,288.2,285.5,282.7
XS GIS Cut Line= 3
     2005572.634      368636.395     2006228.106      368603.171
     2006367.153      368565.926
#Sta/Elev= 30
       0 2664.95    29.8 2655.13    49.7 2649.25    69.6 2643.79    89.5 2639.05
   119.3 2633.87     179 2626.49   198.9 2623.57   218.8 2619.41   288.4 2599.79
   298.3 2595.74   318.2 2585.86   328.2 2582.09   338.1 2579.16     358  2574.7
   427.6 2564.15   517.1 2553.51   556.9  2550.1   616.5 2547.52   624.3 2546.57
   636.4 2545.59   639.3 2546.06   646.4  2547.2   656.3 2549.86   665.9 2551.62
   704.3 2556.45   713.9    2558   723.5 2560.31   733.1 2563.45   800.3 2588.62
#Mann= 3 , 0 , 0
       0      .1       0   624.3    .045       0   639.3      .1       0
Bank Sta=624.3,639.3
XS Rating Curve= 0 ,0
Exp/Cntr=0.3,0.1

Type RM Length L Ch R = 1 ,18558.6 ,154.1,142.6,131.1
XS GIS Cut Line= 2
     2005627.222      368923.476     2006501.235       368776.98
#Sta/Elev= 30
       0 2662.54    19.9 2653.78    79.7 2633.92    99.6 2628.69   119.5 2625.44
   129.4 2624.45   169.3  2623.1   179.2 2621.89   268.8 2599.95   288.8 2597.58
   338.6 2593.86   348.5 2591.52   358.5 2587.48   378.4 2577.13   428.2 2547.73
   438.1 2542.31   448.1 2539.85     458 2539.69   458.5  2539.7   473.5 2539.87
   527.7 2540.75   587.5 2543.02   657.2  2547.1   716.9 2551.39   726.9 2553.23
   736.8 2556.13   836.4 2589.97   846.4 2592.71   866.3    2597   886.2 2603.94
#Mann= 3 , 0 , 0
       0      .1       0   458.5    .045       0   473.5      .1       0
Bank Sta=458.5,473.5
XS Rating Curve= 0 ,0
Exp/Cntr=0.3,0.1

Type RM Length L Ch R = 1 ,18415.8 ,82.4,89.5,99.3
XS GIS Cut Line= 5
     2005886.144       369037.45     2006101.323      369006.151
     2006183.483      368941.598     2006361.495      368884.868
     2006574.718      368832.052
#Sta/Elev= 30
       0 2598.95     9.9 2597.57    19.8 2596.65    69.2 2592.86    79.1 2591.22
      89 2588.26    98.8 2584.57   118.6 2576.53   158.1 2559.77   177.9 2552.32
   187.8 2549.07   207.6 2543.63   217.4 2541.42   236.4 2538.69   245.9 2537.86
   251.9 2537.67   255.4 2537.56   266.9 2537.89   361.3 2541.07   420.3 2543.45
   498.9 2547.35   508.8  2548.6   518.8 2551.17   528.7 2554.68   628.6  2591.3
   638.6 2593.71   648.6 2595.26   658.5 2597.86   718.4 2619.42   728.4 2621.72
#Mann= 3 , 0 , 0
       0      .1       0   251.9    .045       0   266.9      .1       0
Bank Sta=251.9,266.9
XS Rating Curve= 0 ,0
Exp/Cntr=0.3,0.1

Type RM Length L Ch R = 1 ,18326.4 ,296.2,298.9,299
XS GIS Cut Line= 3
     2005660.527      369255.766     2006166.053      369063.736
     2006725.784      368926.994
#Sta/Elev= 30
       0 2656.17    60.1 2646.43    90.1 2640.18   140.2 2627.33   220.3 2603.09
   230.3 2601.46   260.4 2599.78   310.4  2593.3   320.5 2590.53   340.5  2582.2
   390.6 2568.91   430.6 2554.59   460.7 2545.16   480.7 2540.38   510.7 2537.56
   533.3 2533.02   548.3 2533.22   570.6 2533.74   640.1 2531.68   709.6 2535.11
   779.2 2544.54   789.1  2547.7   888.5 2589.08   898.4  2592.3   928.2  2595.4
   948.1 2599.88     968 2607.41   997.8 2620.59  1027.6  2626.6    1117 2649.88
#Mann= 3 , 0 , 0
       0      .1       0   533.3    .045       0   548.3      .1       0
#XS Ineff= 2 , 0
                          585.73         2542.16
Permanent Ineff=
       F       F
Bank Sta=533.3,548.3
XS Rating Curve= 0 ,0
Exp/Cntr=0.3,0.1

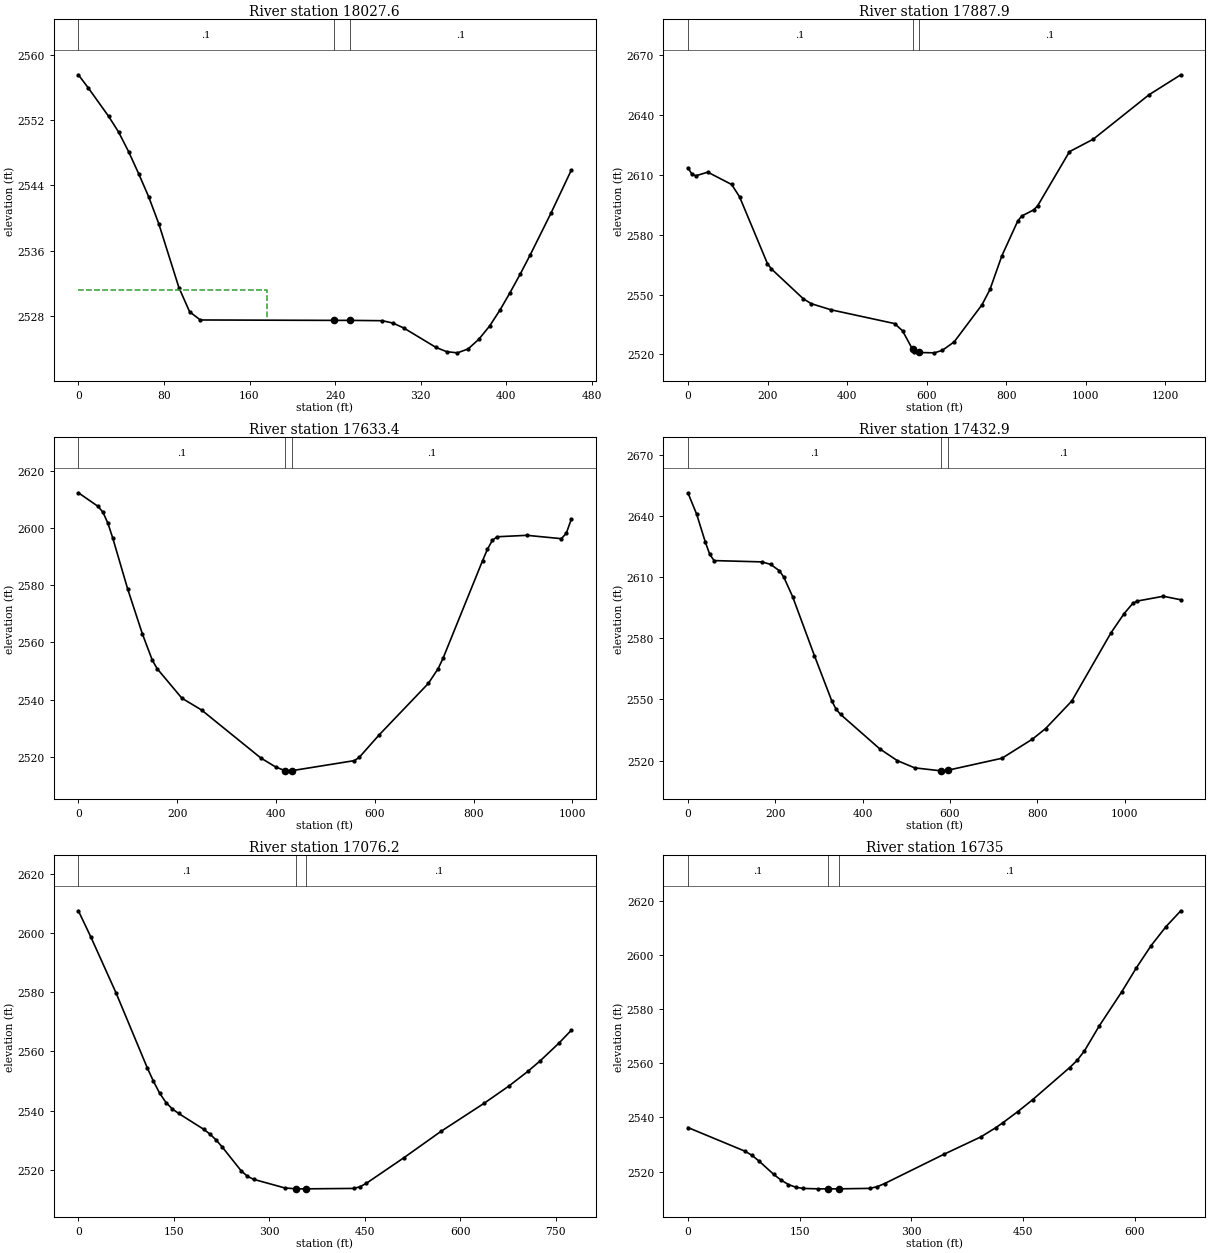
Type RM Length L Ch R = 1 ,18027.6 ,136.8,139.5,142.1
XS GIS Cut Line= 4
     2006069.158      369390.406     2006159.386      369363.998
     2006439.976      369289.174     2006497.194      369238.558
#Sta/Elev= 28
       0 2557.61     9.4 2555.97    28.2 2552.52    37.6 2550.57      47 2548.15
    56.4 2545.44    65.8 2542.59    75.2 2539.29      94 2531.45     104 2528.48
     114 2527.47   238.8 2527.42   253.8 2527.42   284.3 2527.38   294.3 2527.08
   304.3 2526.48   334.3  2524.1   344.4 2523.57   354.4 2523.43   364.4 2523.91
   374.4  2525.1   384.4 2526.71     394 2528.65   403.5 2530.81   413.1 2533.11
   422.6 2535.51   441.7 2540.56   460.8 2545.87
#Mann= 3 , 0 , 0
       0      .1       0   238.8    .045       0   253.8      .1       0
#XS Ineff= 2 , 0
          176.65 2531.18
Permanent Ineff=
       F       F
Bank Sta=238.8,253.8
XS Rating Curve= 0 ,0
Exp/Cntr=0.3,0.1

Type RM Length L Ch R = 1 ,17887.9 ,249.9,254.5,259.3
XS GIS Cut Line= 2
     2005832.363      369508.266     2007058.206      369332.547
#Sta/Elev= 30
       0 2613.48      10 2610.32      20 2609.49    49.9  2611.3   109.9 2605.12
   129.8 2598.94   199.7 2565.54   209.7 2562.84   289.6 2547.94   309.6 2545.44
   359.5 2542.35   519.3 2535.45   539.3 2531.84   564.6 2522.49   569.2 2521.08
   579.6 2520.97   619.2 2520.79   639.2 2522.02   669.1 2526.29     739 2544.89
     759 2552.55     789 2569.46   828.9 2586.87   838.9 2589.33   868.9 2592.41
   878.8 2594.45   958.7 2621.56  1018.7 2627.84  1158.5 2650.05  1238.4 2660.08
#Mann= 3 , 0 , 0
       0      .1       0   564.6    .045       0   579.6      .1       0
Bank Sta=564.6,579.6
XS Rating Curve= 0 ,0
Exp/Cntr=0.3,0.1

Type RM Length L Ch R = 1 ,17633.4 ,199.5,200.1,200.2
XS GIS Cut Line= 2
     2005901.943      369626.943     2006895.865      369714.887
#Sta/Elev= 30
       0 2612.31    39.9 2607.55    49.9 2605.46    59.9  2601.6    69.8 2596.38
    99.8 2578.69   129.7 2562.94   149.7 2553.79   159.6 2550.81   209.5 2540.53
   249.4 2536.39   369.2 2519.64   399.1 2516.51   417.7 2515.23   429.1 2515.13
   432.7  2515.2   558.8  2518.7   568.8 2519.87   608.7 2527.65   708.4 2545.66
   728.4 2550.86   738.4 2554.52   818.2 2588.55   828.2 2592.59   838.2 2595.72
   848.1 2596.94     908 2597.44   977.8 2596.27   987.8 2598.17   997.8    2603
#Mann= 3 , 0 , 0
       0      .1       0   417.7    .045       0   432.7      .1       0
Bank Sta=417.7,432.7
XS Rating Curve= 0 ,0
Exp/Cntr=0.3,0.1

Type RM Length L Ch R = 1 ,17432.9 ,358.5,356.2,353.8
XS GIS Cut Line= 2
     2005764.983      369835.101     2006893.485      369838.452
#Sta/Elev= 30
       0 2651.25      20 2640.77      40 2627.02    49.9 2621.11    59.9 2618.02
   169.8 2617.38   189.8 2616.11   209.7    2613   219.7 2609.84   239.7 2600.38
   289.6 2571.48   329.6 2549.16   339.6  2545.1   349.5 2542.64   439.4 2525.74
   479.4    2520   519.3 2516.45   579.2 2514.99     580    2515     595 2515.28
     719 2521.15     789 2530.56   818.9 2535.68   878.8 2549.17   968.7 2582.62
   998.7 2592.03  1018.6 2597.04  1028.6 2598.18  1088.6 2600.54  1128.5 2598.82
#Mann= 3 , 0 , 0
       0      .1       0     580    .045       0     595      .1       0
Bank Sta=580,595
XS Rating Curve= 0 ,0
Exp/Cntr=0.3,0.1

Type RM Length L Ch R = 1 ,17076.2 ,335.7,340.6,345.1
XS GIS Cut Line= 3
     2005935.923      370124.658     2006417.647      370112.665
      2006709.48      370134.652
#Sta/Elev= 30
       0 2607.52    19.7 2598.62      59 2579.89   108.2 2554.52     118 2549.94
   127.8  2545.9   137.7 2542.76   147.5 2540.64   157.4  2539.1   196.7 2533.76
   206.5 2532.16   216.4 2530.14   226.2 2527.71   255.7 2519.74   265.5 2517.89
   275.4 2516.83   324.5 2513.92     342 2513.62     357 2513.62   432.7 2513.76
   442.5 2514.32   452.4 2515.47   511.1 2524.06   569.7 2533.01     638 2542.57
     677 2548.41   706.2 2553.26   725.8 2556.86     755 2562.79   774.5 2567.15
#Mann= 3 , 0 , 0
       0      .1       0     342    .045       0     357      .1       0
Bank Sta=342,357
XS Rating Curve= 0 ,0
Exp/Cntr=0.3,0.1

Type RM Length L Ch R = 1 ,16735   ,272,283.6,293.3
XS GIS Cut Line= 3
     2006129.812      370300.557     2006233.753      370284.566
     2006781.438      370384.509
#Sta/Elev= 30
       0 2536.27    76.5 2527.54      86 2526.01    95.6 2523.86   115.1 2518.99
     125 2516.86     135 2515.21   144.9 2514.21   154.9 2513.77   174.8 2513.62
   187.9 2513.62   202.9 2513.62   244.4 2513.79   254.3 2514.42   264.2 2515.58
   343.8 2526.38   393.5 2532.82   413.4  2536.2   423.3 2538.11   443.2 2542.18
   463.1 2546.58   512.8 2558.44   522.7 2561.06   532.6 2564.61   552.5 2573.84
   582.4  2586.3   602.2 2595.22   622.1 2603.48     642 2610.46   661.9 2616.33
#Mann= 3 , 0 , 0
       0      .1       0   187.9    .045       0   202.9      .1       0
Bank Sta=187.9,202.9
XS Rating Curve= 0 ,0
Exp/Cntr=0.3,0.1

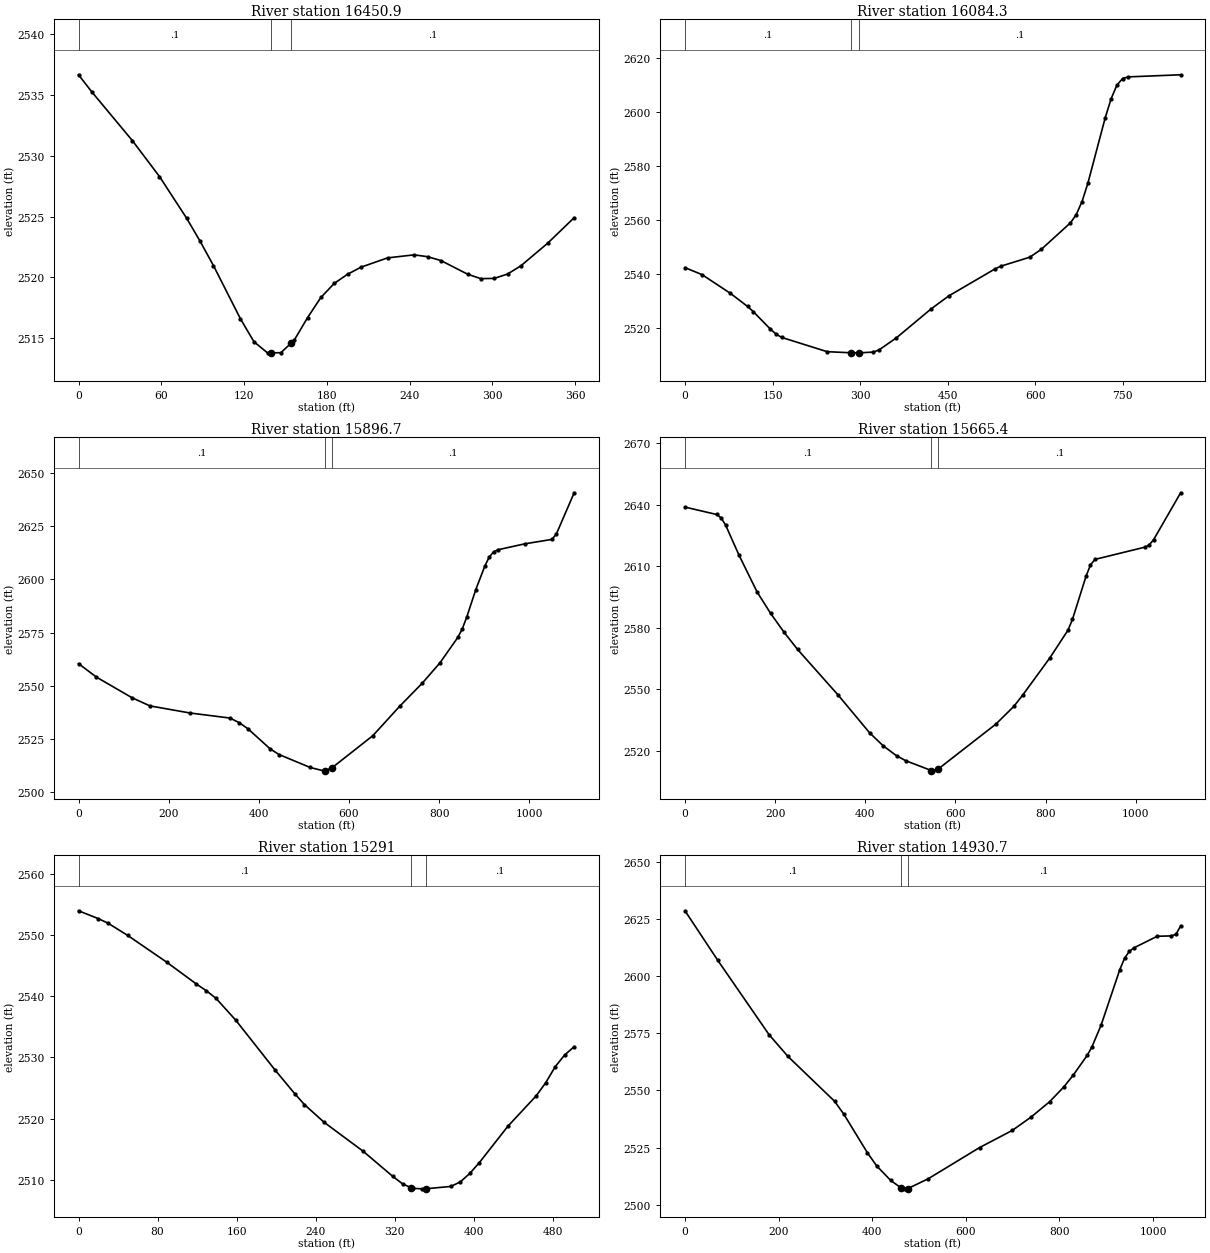
Type RM Length L Ch R = 1 ,16450.9 ,379.6,366.3,349.7
XS GIS Cut Line= 3
     2006085.837      370438.478     2006219.761      370498.444
     2006401.656       370608.38
#Sta/Elev= 30
       0 2536.68     9.8 2535.25    39.1 2531.25    58.7  2528.3    78.3 2524.88
      88    2523    97.8 2520.97   117.4 2516.58   127.2 2514.69     137 2513.78
   139.2 2513.78   146.7 2513.79   154.2 2514.59   156.4 2514.83   166.1 2516.69
   175.7 2518.34   185.4  2519.5     195 2520.25   204.7 2520.83     224  2521.6
   243.3 2521.85     253  2521.7   262.7 2521.38     282 2520.26   291.6 2519.89
   301.3 2519.91     311 2520.27   320.6 2520.94     340  2522.8   359.3 2524.91
#Mann= 3 , 0 , 0
       0      .1       0   139.2    .045       0   154.2      .1       0
Bank Sta=139.2,154.2
XS Rating Curve= 0 ,0
Exp/Cntr=0.3,0.1

Type RM Length L Ch R = 1 ,16084.3 ,186.7,187.3,188.6
XS GIS Cut Line= 3
     2005995.889       370836.25     2006263.735       370784.28
     2006831.301      370683.191
#Sta/Elev= 30
       0 2542.34    29.2 2539.75      78 2532.79   107.2 2527.96   116.9 2526.07
   146.2 2519.59   155.9 2517.75   165.6 2516.49   243.6  2511.2     284  2510.8
     299 2510.77   322.5 2511.05   332.5 2511.85   362.3 2516.33   421.9 2527.08
   451.8 2531.83   531.3 2541.87   541.2 2542.87   590.9 2546.21   610.8 2549.16
   660.5 2558.93   670.4 2561.97   680.4 2566.84   690.3 2573.56   720.1 2597.88
   730.1 2604.85     740 2609.92   749.9 2612.41   759.9 2613.01   849.3 2613.79
#Mann= 3 , 0 , 0
       0      .1       0     284    .045       0     299      .1       0
Bank Sta=284,299
XS Rating Curve= 0 ,0
Exp/Cntr=0.3,0.1

Type RM Length L Ch R = 1 ,15896.7 ,235.1,231.3,226.7
XS GIS Cut Line= 3
     2005769.814      371034.495     2006317.704      370956.181
     2006860.477      370898.434
#Sta/Elev= 30
       0 2560.44    39.5 2554.13   118.6 2544.42   158.1 2540.58   247.1 2537.24
     336 2534.85   355.8 2532.75   375.6 2529.86     425 2520.38   444.7 2517.72
   513.9 2511.62   543.6 2510.05   546.4 2510.13   561.4 2511.34   652.7 2526.56
   712.2 2540.37   761.9 2551.13   801.6 2560.78   841.3 2572.77   851.2  2576.8
   861.1 2582.32     881 2595.14   900.8  2606.1   910.7 2610.46   920.7 2612.97
   930.6 2613.96   990.1 2616.74  1049.7  2618.8  1059.6 2621.25  1099.3 2640.72
#Mann= 3 , 0 , 0
       0      .1       0   546.4    .045       0   561.4      .1       0
Bank Sta=546.4,561.4
XS Rating Curve= 0 ,0
Exp/Cntr=0.3,0.1

Type RM Length L Ch R = 1 ,15665.4 ,381.2,374.1,371.4
XS GIS Cut Line= 2
     2005828.635      371342.473     2006878.717      371015.704
#Sta/Elev= 30
       0 2638.82      70 2635.22      80 2633.58      90 2630.11     120 2615.32
     160 2597.42     190 2586.96     220 2577.72   249.9 2569.36   339.9 2547.11
   409.9 2528.64   439.9 2522.34   469.9 2517.44   489.9 2515.09   546.9 2510.28
   549.9 2510.15   561.9 2511.04   689.8 2532.94   729.8 2541.62   749.8 2547.23
   809.8 2565.31   849.8 2578.75   859.8 2584.04   889.8 2605.03   899.8 2610.64
   909.8 2613.31  1019.8 2619.23  1029.8  2620.3  1039.8  2622.9  1099.8  2645.8
#Mann= 3 , 0 , 0
       0      .1       0   546.9    .045       0   561.9      .1       0
Bank Sta=546.9,561.9
XS Rating Curve= 0 ,0
Exp/Cntr=0.3,0.1

Type RM Length L Ch R = 1 ,15291   ,364.3,359.1,327.5
XS GIS Cut Line= 3
     2006213.764      371705.751     2006497.291      371503.655
     2006623.529      371415.917
#Sta/Elev= 30
       0 2553.92    19.9 2552.65    29.8  2551.9    49.7 2549.91    89.5 2545.51
   119.4 2541.96   129.3 2540.89   139.3 2539.62   159.2 2536.07     199 2527.94
   218.9 2524.08   228.8 2522.29   248.7  2519.4   288.5 2514.64   318.3 2510.56
   328.3 2509.33     337 2508.71   338.2 2508.62   348.2 2508.54     352 2508.56
     377 2508.93   386.6 2509.67   396.2 2511.05   405.8  2512.8   434.7 2518.74
   463.5 2523.73   473.1 2525.86   482.7 2528.47   492.3 2530.39   501.9 2531.74
#Mann= 3 , 0 , 0
       0      .1       0     337    .045       0     352      .1       0
Bank Sta=337,352
XS Rating Curve= 0 ,0
Exp/Cntr=0.3,0.1

Type RM Length L Ch R = 1 ,14930.7 ,325.7,330.1,334.2
XS GIS Cut Line= 2
     2006423.644      372095.528     2006992.595      371202.358
#Sta/Elev= 30
       0 2628.65    69.9 2607.01   179.8 2574.39   219.8 2564.95   319.7 2545.27
   339.7 2539.53   389.6 2522.81   409.6    2517   439.6 2510.63   461.1 2507.47
   469.6 2506.96   476.1 2507.07   519.5 2511.35   629.4 2525.02   699.3 2532.53
   739.3 2538.34   779.3 2545.12   809.2 2551.51   829.2 2556.62   859.2 2565.34
   869.2 2568.93   889.2 2578.68   929.1 2602.92   939.1  2607.8   949.1 2610.84
   959.1 2612.42    1009 2617.49    1039 2617.66    1049 2618.34    1059 2622.04
#Mann= 3 , 0 , 0
       0      .1       0   461.1    .045       0   476.1      .1       0
Bank Sta=461.1,476.1
XS Rating Curve= 0 ,0
Exp/Cntr=0.3,0.1

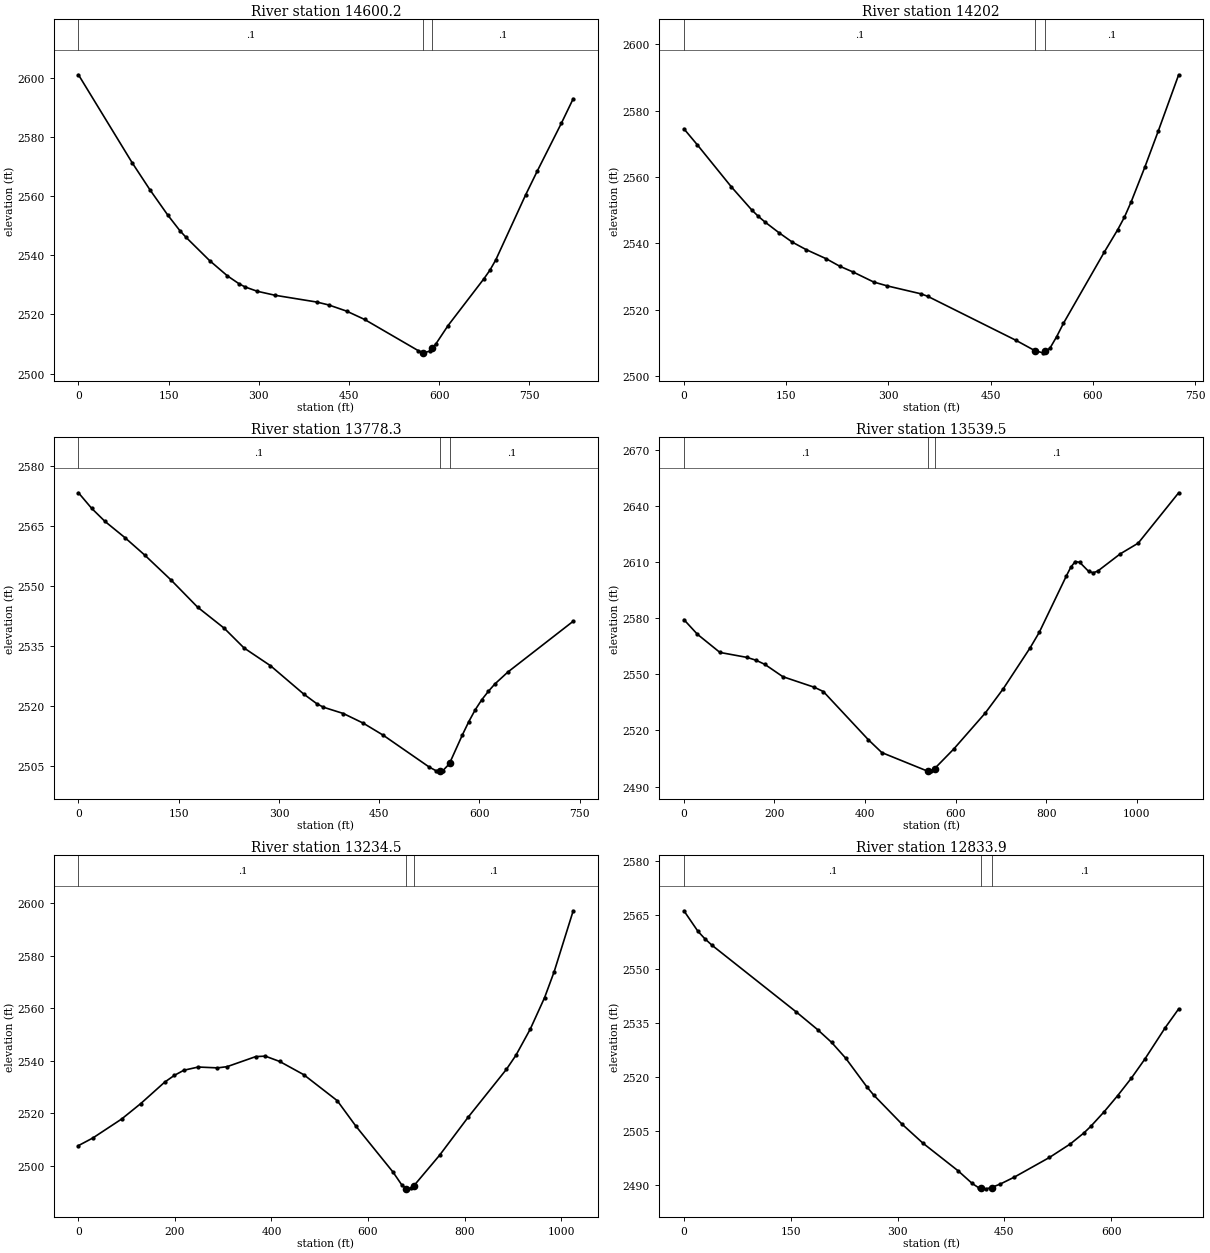
Type RM Length L Ch R = 1 ,14600.2 ,397.2,398.2,399.2
XS GIS Cut Line= 2
     2006562.129      372241.334     2007137.901      371653.115
#Sta/Elev= 30
       0 2600.92    89.2 2571.25     119 2562.04   148.8 2553.46   168.6 2548.29
   178.5  2546.1   218.2 2538.14   247.9 2532.97   267.8 2530.23   277.7  2529.2
   297.5 2527.78   327.3 2526.42   396.7 2524.13   416.5 2523.15   446.3 2521.06
     476 2518.26   565.3 2507.72   573.9 2507.08   575.2 2506.98   585.1 2507.64
   588.9 2508.59     595 2510.11   614.9  2516.2   674.4 2531.97   684.3 2534.83
   694.2 2538.34   743.8 2560.28   763.6 2568.51   803.3  2584.5   823.1 2592.83
#Mann= 3 , 0 , 0
       0      .1       0   573.9    .045       0   588.9      .1       0
Bank Sta=573.9,588.9
XS Rating Curve= 0 ,0
Exp/Cntr=0.3,0.1

Type RM Length L Ch R = 1 ,14202   ,431.7,423.7,417.5
XS GIS Cut Line= 2
     2006847.213      372471.015     2007377.763      371975.596
#Sta/Elev= 30
       0 2574.53    19.9 2569.65    69.6 2557.03    99.4  2550.1   109.4  2548.1
   119.3 2546.38   139.2 2543.25   159.1 2540.36     179 2538.15   208.8 2535.36
   228.7  2533.1   248.6 2531.33   278.4 2528.35   298.3 2527.18     348 2524.78
     358 2524.01   487.2 2510.77   515.4  2507.6     527    2507   530.4 2507.47
     537 2508.38   546.9 2511.88   556.8 2515.88   616.5 2537.27   636.4  2544.1
   646.3 2547.89   656.3 2552.56   676.2 2562.95   696.1 2573.93   725.9 2590.82
#Mann= 3 , 0 , 0
       0      .1       0   515.4    .045       0   530.4      .1       0
Bank Sta=515.4,530.4
XS Rating Curve= 0 ,0
Exp/Cntr=0.3,0.1

Type RM Length L Ch R = 1 ,13778.3 ,231.1,238.8,244.6
XS GIS Cut Line= 3
     2007301.953      372885.397     2007537.502      372394.012
     2007638.802      372227.079
#Sta/Elev= 30
       0 2573.32    19.8 2569.41    39.6 2566.16    69.4  2562.1    99.1 2557.72
   138.7 2551.44   178.3 2544.66     218  2539.4   247.7 2534.45   287.3    2530
   336.9 2522.92   356.7 2520.47   366.6  2519.6   396.3 2518.03     426 2515.62
   455.8 2512.61   525.1 2504.58     535  2503.7   540.7 2503.68   544.9 2503.67
   554.7 2505.39   555.7 2505.74   574.2  2512.6     584    2516   593.7 2518.99
   603.5  2521.5   613.3 2523.59     623 2525.43   642.6 2528.44   740.2 2541.14
#Mann= 3 , 0 , 0
       0      .1       0   540.7    .045       0   555.7      .1       0
Bank Sta=540.7,555.7
XS Rating Curve= 0 ,0
Exp/Cntr=0.3,0.1

Type RM Length L Ch R = 1 ,13539.5 ,300.5,304.9,309.3
XS GIS Cut Line= 2
     2007329.928      372917.732     2008116.164      372158.717
#Sta/Elev= 30
       0 2579.14    29.8 2571.32    79.5 2561.62   139.1 2558.97     159 2557.48
   178.8 2555.23   218.6 2548.65   288.1 2543.01     308 2540.72   407.3    2515
   437.1 2508.12   536.5 2498.37   538.7 2498.41   546.4 2498.54   553.7 2499.56
   596.1 2510.05   665.6 2529.24   705.4 2542.23     765 2564.19   784.8 2572.32
   844.5 2602.37   854.4 2607.07   864.3 2610.18   874.3 2609.74   894.1 2604.87
   904.1 2604.19     914 2605.06   963.7 2614.26  1003.4 2619.99  1092.8  2646.9
#Mann= 3 , 0 , 0
       0      .1       0   538.7    .045       0   553.7      .1       0
Bank Sta=538.7,553.7
XS Rating Curve= 0 ,0
Exp/Cntr=0.3,0.1

Type RM Length L Ch R = 1 ,13234.5 ,432.3,400.3,368.4
XS GIS Cut Line= 4
     2007761.543       373393.45     2007786.533      372857.841
     2007948.103      372753.817     2008073.364      372484.638
#Sta/Elev= 30
       0  2507.7    29.8  2510.6    89.4 2517.82   129.1 2523.72   178.7 2531.89
   198.6 2534.45   218.4 2536.42   248.2 2537.64     288 2537.32   307.8 2537.77
   367.4 2541.62   387.2 2541.79     417 2539.76   466.7 2534.74   536.2 2524.83
   574.6 2515.18   651.5 2497.68   670.7 2492.53   679.5 2491.33   680.3 2491.22
   689.9 2491.49   694.5 2492.28   748.2    2504   807.5 2518.52   886.7 2536.74
   906.5 2542.12   936.2 2552.09   965.9  2564.1   985.7 2573.95  1025.2 2597.19
#Mann= 3 , 0 , 0
       0      .1       0   679.5    .045       0   694.5      .1       0
Bank Sta=679.5,694.5
XS Rating Curve= 0 ,0
Exp/Cntr=0.3,0.1

Type RM Length L Ch R = 1 ,12833.9 ,292.6,293.9,295.1
XS GIS Cut Line= 3
     2008338.545       373294.84     2008133.436       372802.79
     2008136.661      372641.215
#Sta/Elev= 30
       0 2566.18    19.7 2560.47    29.6 2558.37    39.5 2556.59     158 2538.03
   187.6 2533.18   207.3 2529.63   227.1 2525.24   256.7 2517.31   266.5 2514.98
     306 2506.95   335.6 2501.62     385 2493.94   404.8 2490.42   414.6 2489.14
   416.9 2489.09   424.5 2488.93   431.9  2489.3   444.2 2490.26     464 2492.19
   513.3 2497.65   542.6 2501.41   561.6 2504.45   571.1 2506.25   590.1 2510.35
   609.1 2514.84   628.2 2519.66   647.2 2524.97   675.7 2533.67   694.7 2538.92
#Mann= 3 , 0 , 0
       0      .1       0   416.9    .045       0   431.9      .1       0
Bank Sta=416.9,431.9
XS Rating Curve= 0 ,0
Exp/Cntr=0.3,0.1

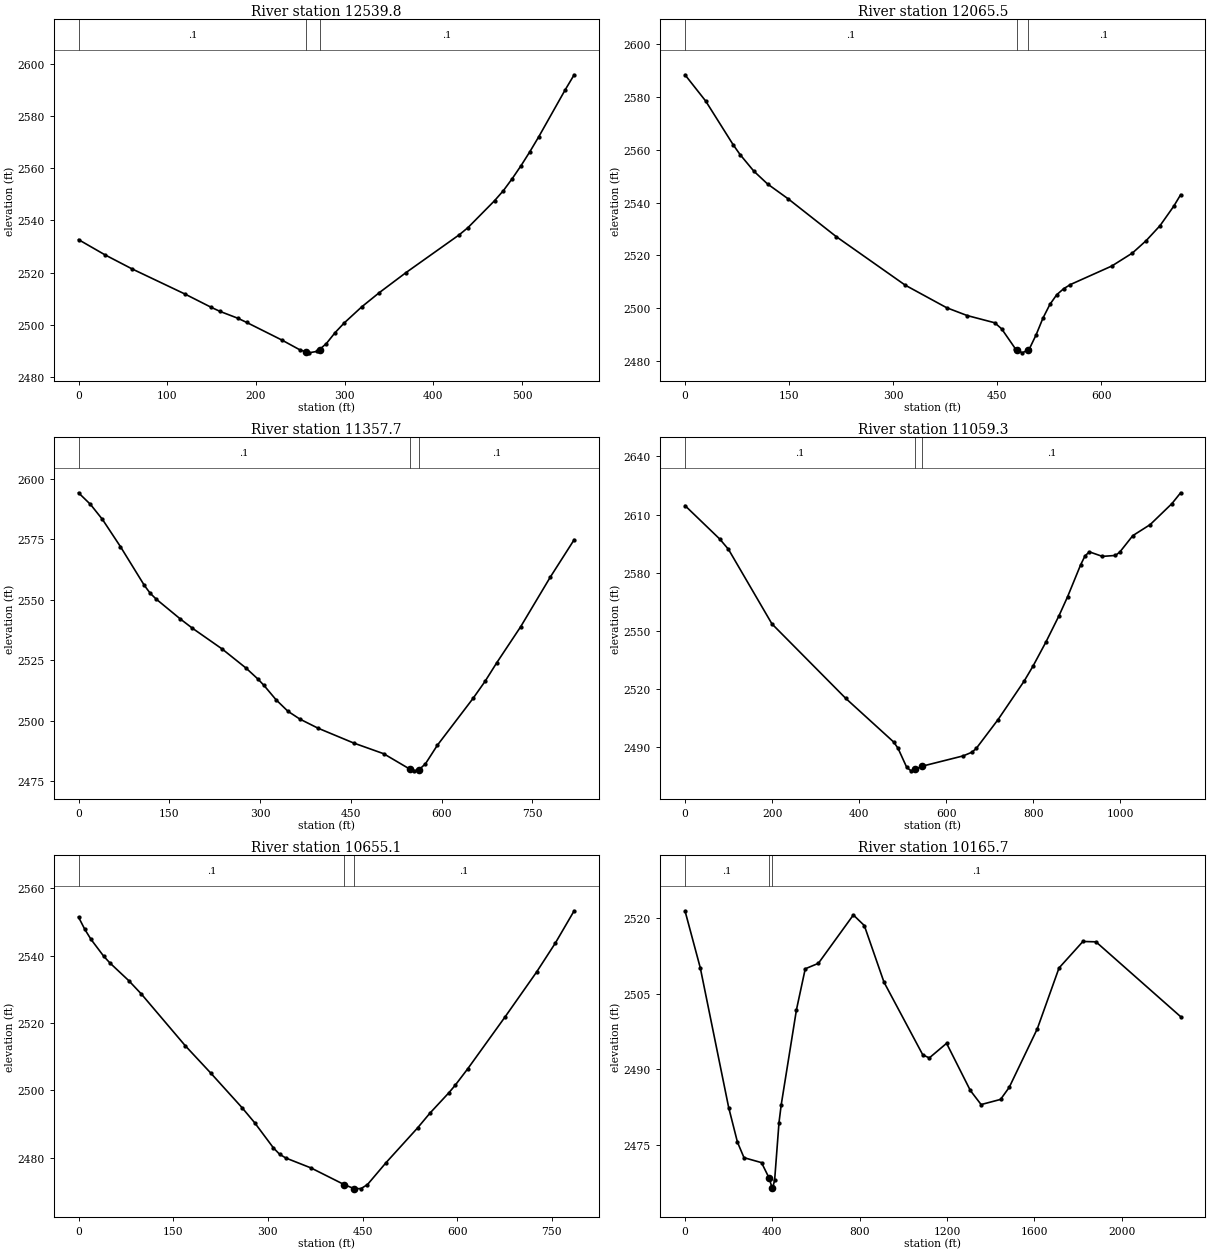
Type RM Length L Ch R = 1 ,12539.8 ,479.3,474,468.7
XS GIS Cut Line= 2
     2008510.447         373015.     2008326.552      372487.303
#Sta/Elev= 30
       0 2532.63    29.9 2526.78    59.9 2521.47   119.8 2511.78   149.7 2506.63
   159.7 2505.06   179.6 2502.46   189.6 2500.85   229.5 2494.05   249.5 2490.34
   256.7  2489.5   259.4 2489.18   269.4 2489.76   271.7 2490.45   279.4 2492.74
   289.4 2496.98   299.4  2500.6   319.3 2506.83   339.3 2512.33   369.2 2519.97
   429.1 2534.45   439.1 2537.24     469 2547.55     479 2551.43     489 2556.05
     499 2561.06   508.9  2566.4   518.9 2572.12   548.8 2590.18   558.8 2595.89
#Mann= 3 , 0 , 0
       0      .1       0   256.7    .045       0   271.7      .1       0
Bank Sta=256.7,271.7
XS Rating Curve= 0 ,0
Exp/Cntr=0.3,0.1

Type RM Length L Ch R = 1 ,12065.5 ,703.6,707.6,711
XS GIS Cut Line= 2
     2009076.122      372993.013     2008694.341      372389.359
#Sta/Elev= 30
       0 2588.44    29.8  2578.5    69.4 2561.93    79.4 2558.19    99.2 2551.91
     119 2547.04   148.8 2541.39   218.2 2527.04   317.4 2508.68     377 2500.14
   406.7 2497.16   446.4 2494.42   456.3 2492.12   476.2 2484.54   479.1  2484.1
   486.1 2483.03   494.1 2484.15     496 2484.41   505.9 2489.82   515.8 2496.18
   525.8 2501.38   535.7 2505.07   545.6 2507.33   555.5 2508.93     615 2515.94
   644.8 2520.88   664.6 2525.58   684.5 2531.24   704.3 2538.62   714.2 2542.97
#Mann= 3 , 0 , 0
       0      .1       0   479.1    .045       0   494.1      .1       0
Bank Sta=479.1,494.1
XS Rating Curve= 0 ,0
Exp/Cntr=0.3,0.1

Type RM Length L Ch R = 1 ,11357.7 ,294.3,298.4,303
XS GIS Cut Line= 3
      2009481.89      372731.163     2009286.225      372223.817
     2009176.065      371971.599
#Sta/Elev= 30
       0 2594.15    19.8 2589.34    39.6 2583.14    69.2 2571.95   108.8 2555.91
   118.6 2552.63   128.5 2550.23   168.1 2542.08   187.8 2538.31   237.3 2529.67
   276.8 2521.78   296.6 2517.22   306.5 2514.62   326.3 2508.73     346 2503.96
   365.8 2500.72   395.5    2497   454.8 2490.83   504.2 2486.43   547.5 2480.06
   553.6 2479.36   562.5 2479.79   573.3 2482.28   592.9 2489.91   651.9 2509.26
   671.6 2516.25   691.2 2524.03   730.5 2538.81   779.7  2559.4     819 2574.77
#Mann= 3 , 0 , 0
       0      .1       0   547.5    .045       0   562.5      .1       0
Bank Sta=547.5,562.5
XS Rating Curve= 0 ,0
Exp/Cntr=0.3,0.1

Type RM Length L Ch R = 1 ,11059.3 ,400.3,403.9,407.6
XS GIS Cut Line= 2
      2009673.11      372764.982     2009436.426      371651.736
#Sta/Elev= 30
       0 2614.63    79.9 2597.32    99.8 2592.04   199.7 2553.49   369.4 2514.95
   479.2 2492.46   489.2 2489.21   509.2 2479.34   519.2 2477.56   529.3 2478.29
   544.3 2479.94     639  2485.3   658.9 2487.19   668.9 2489.16   718.8 2504.02
   778.7  2523.9   798.7  2531.5   828.6 2544.04   858.6 2557.61   878.6 2567.56
   908.5 2584.02   918.5  2588.6   928.5 2590.72   958.4 2588.37   988.4 2588.86
   998.4  2590.6  1028.3  2599.1  1068.2  2604.8  1118.2 2615.67  1138.1 2621.24
#Mann= 3 , 0 , 0
       0      .1       0   529.3    .045       0   544.3      .1       0
Bank Sta=529.3,544.3
XS Rating Curve= 0 ,0
Exp/Cntr=0.3,0.1

Type RM Length L Ch R = 1 ,10655.1 ,492.2,488.5,484.9
XS GIS Cut Line= 3
     2009869.667      372565.258      2009926.93      372241.606
      2009899.65      371785.705
#Sta/Elev= 30
       0 2551.42      10 2547.77    19.9 2544.78    39.8 2539.84    49.8  2537.8
    79.7 2532.55    99.6 2528.59   169.3 2513.22   209.2 2505.21     259  2494.9
   278.9 2490.46   308.8 2482.95   318.7 2481.04   328.7 2479.92   368.4 2476.99
   421.4 2472.01   436.4 2470.88   437.9 2470.79   447.8 2470.89   457.8 2472.04
   487.5  2478.6   537.2 2488.85     557 2493.28   586.8 2499.28   596.8 2501.51
   616.6 2506.37   676.2 2521.88   725.8  2535.1   755.6 2543.72   785.4 2553.29
#Mann= 3 , 0 , 0
       0      .1       0   421.4    .045       0   436.4      .1       0
Bank Sta=421.4,436.4
XS Rating Curve= 0 ,0
Exp/Cntr=0.3,0.1

Type RM Length L Ch R = 1 ,10165.7 ,413,430.3,447.7
XS GIS Cut Line= 4
     2010388.036      372424.006     2010181.719       371536.14
     2009848.725      370963.362     2009687.843       370285.83
#Sta/Elev= 30
       0 2521.42    70.1 2510.12   200.3 2482.43   240.4 2475.59   270.4 2472.52
   350.6 2471.54   384.7 2468.55   399.7 2466.48   400.7 2466.35   410.7 2468.09
   430.7 2479.48   440.7 2482.96   510.8 2501.86   550.9 2509.93     611 2511.01
   771.3 2520.59   821.4  2518.5   911.5 2507.29  1089.5 2492.87  1119.2 2492.28
  1198.3 2495.17  1307.1 2485.83  1356.5 2483.04  1445.5 2484.06  1485.1 2486.44
  1613.9 2498.05  1713.3 2510.09  1822.8 2515.34  1882.5 2515.27  2270.4 2500.45
#Mann= 3 , 0 , 0
       0      .1       0   384.7    .045       0   399.7      .1       0
Bank Sta=384.7,399.7
XS Rating Curve= 0 ,0
Exp/Cntr=0.3,0.1