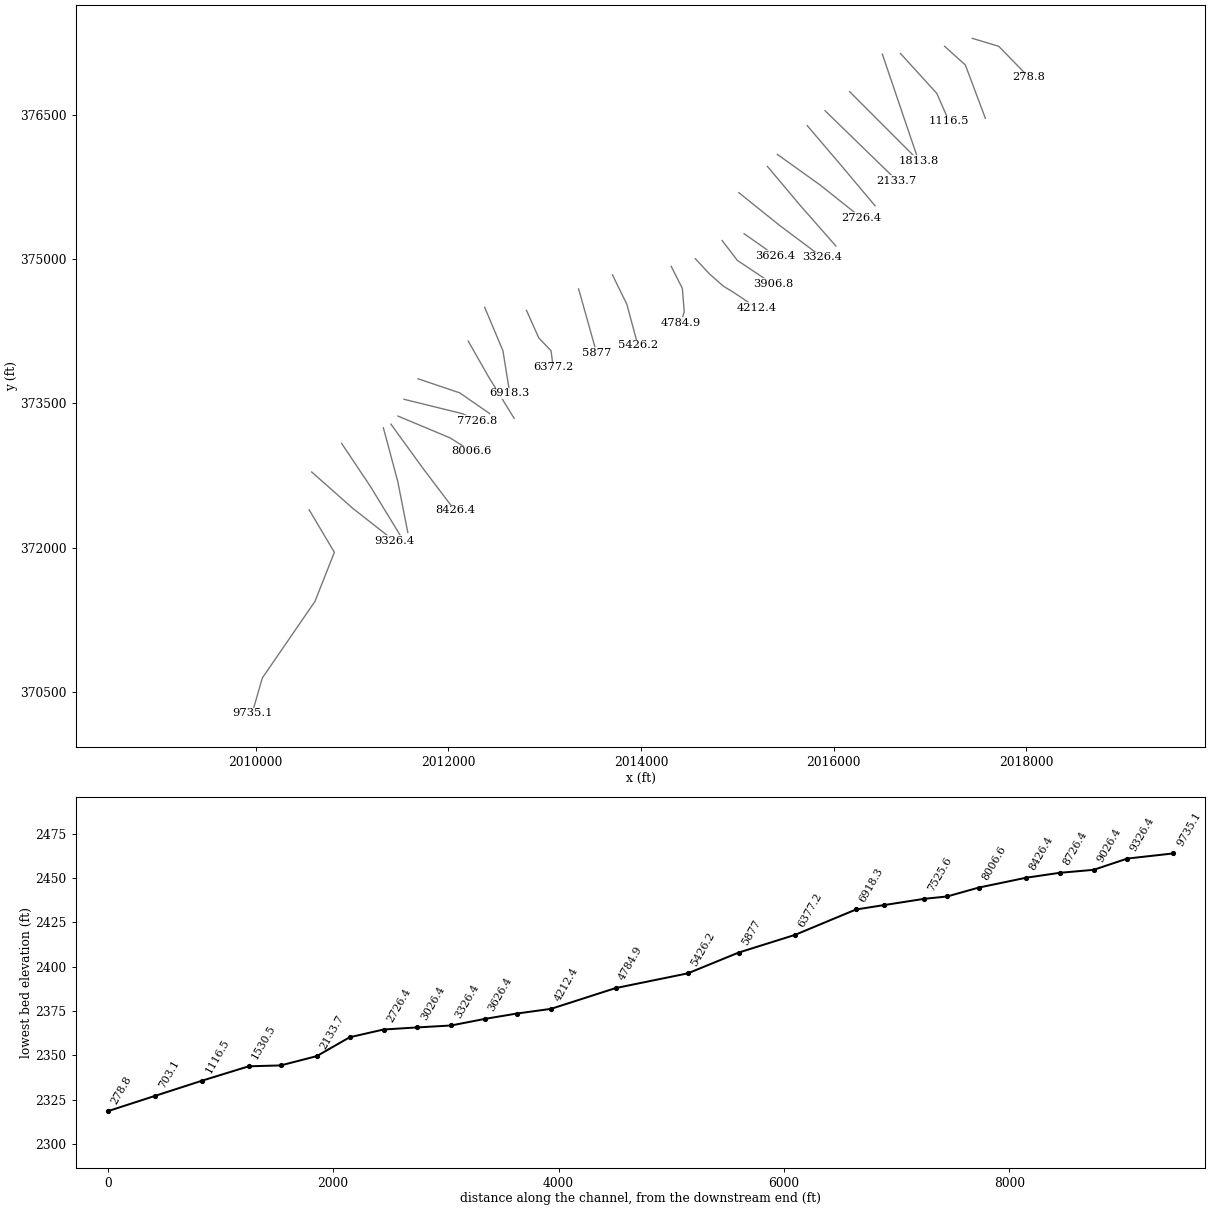
HEC-RAS study LaurelCrk5.prj: LaurelCrk5

--- LaurelCrk5.g01 (geometry) --- (continued)

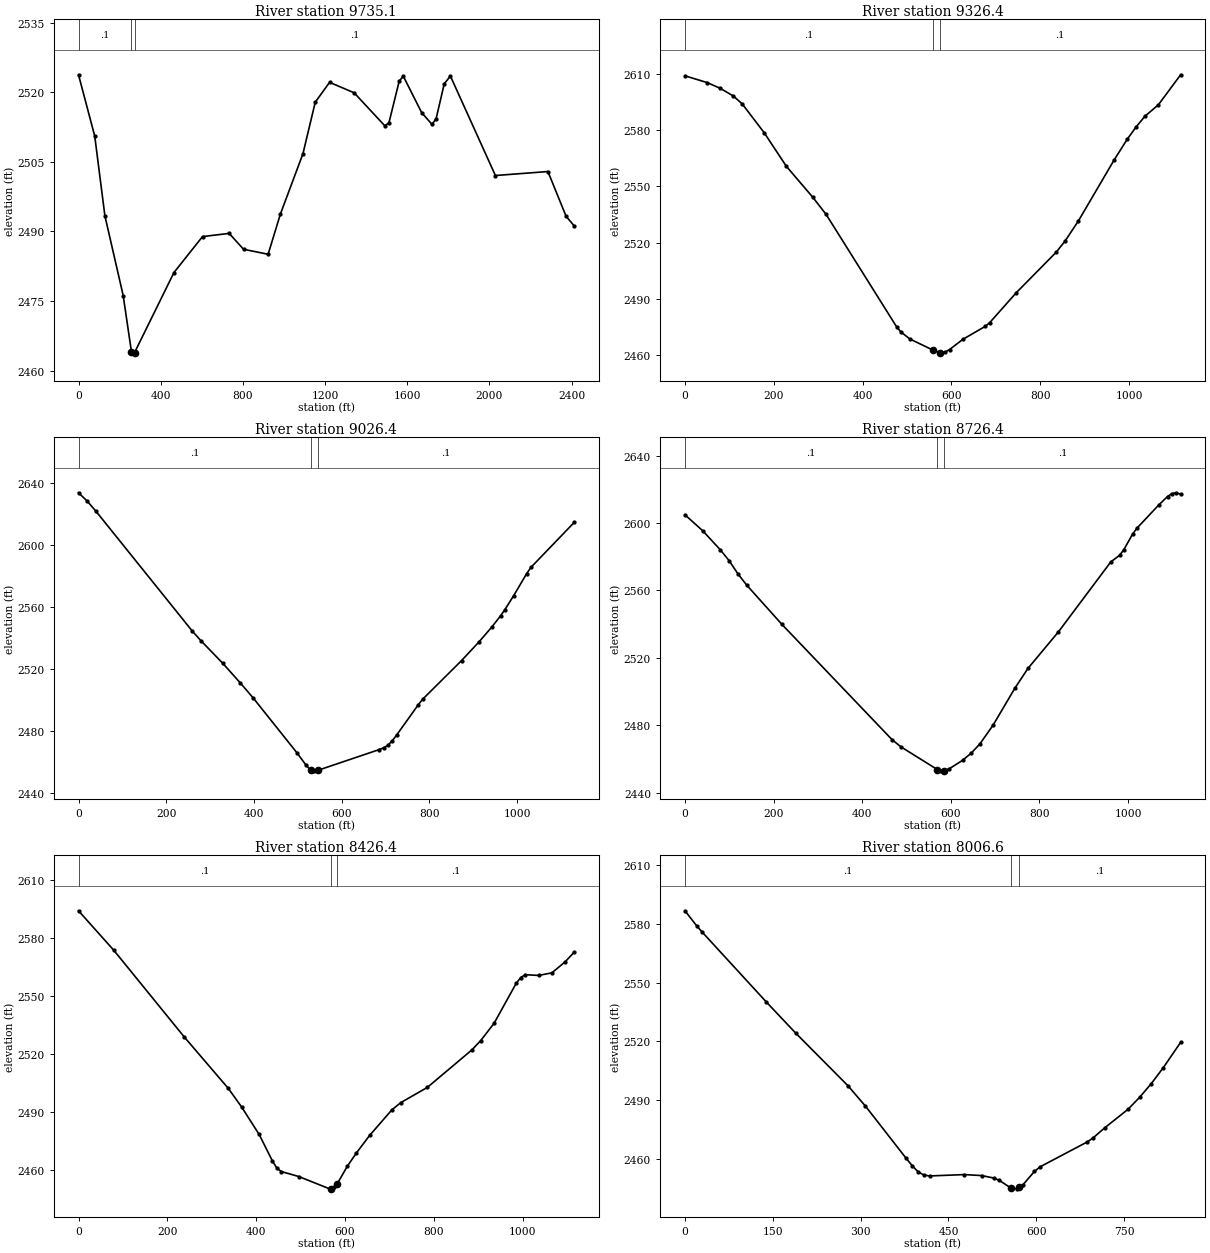
Type RM Length L Ch R = 1 ,9735.1  ,401.9,408.8,417.1
XS GIS Cut Line= 5
     2010553.941      372393.357     2010815.608       371951.23
     2010614.523      371440.706      2010067.79      370643.746
     2009961.708      370275.397
#Sta/Elev= 30
       0 2523.76      79 2510.54   128.4 2493.37   217.4 2476.19   257.7 2464.04
   266.8 2463.84   272.7 2463.88   464.4 2481.14   603.5 2488.89   733.2 2489.58
   803.1 2486.16   922.8 2485.08   982.6 2493.76  1092.4 2506.77  1152.1 2517.85
  1221.9 2522.13  1341.4 2519.88  1490.9 2512.75  1510.8 2513.42  1560.6 2522.38
  1580.6 2523.46  1670.2 2515.59    1720 2513.09    1740 2514.23  1779.8  2521.8
  1809.7  2523.5  2028.9 2502.05  2284.5 2502.91  2372.9 2493.27  2412.2 2491.21
#Mann= 3 , 0 , 0
       0      .1       0   257.7    .045       0   272.7      .1       0
Bank Sta=257.7,272.7
XS Rating Curve= 0 ,0
Exp/Cntr=0.3,0.1

Type RM Length L Ch R = 1 ,9326.4  ,305.3,299.6,291.6
XS GIS Cut Line= 3
     2010580.771      372786.668     2011004.118      372410.973
     2011436.557      372070.498
#Sta/Elev= 30
       0 2609.22    49.6 2605.63    79.4 2602.54   109.2 2598.37   129.1 2594.14
   178.7 2578.67   228.4 2560.78     288 2544.18   317.8 2535.08   476.6 2474.89
   486.6 2472.07   506.4 2468.38   558.5 2462.41   573.5 2461.06     576 2460.94
     586 2461.37     596 2462.71     626 2468.19   676.1 2475.08   686.1 2477.03
   746.1  2493.1   836.2 2514.82   856.2 2520.82   886.2 2531.59   966.3 2564.06
   996.3 2575.34  1016.3 2581.93  1036.3 2587.65  1066.4 2593.75  1116.4 2609.78
#Mann= 3 , 0 , 0
       0      .1       0   558.5    .045       0   573.5      .1       0
Bank Sta=558.5,573.5
XS Rating Curve= 0 ,0
Exp/Cntr=0.3,0.1

Type RM Length L Ch R = 1 ,9026.4  ,306.7,300,292.1
XS GIS Cut Line= 3
     2010892.141      373083.066     2011190.447       372635.61
     2011498.573      372129.415
#Sta/Elev= 30
       0 2633.52    19.9 2628.15    39.8 2621.63   258.9 2544.72   278.8 2538.44
   328.6  2523.9   368.5 2511.31   398.4 2501.48   497.9 2466.28   517.9 2458.63
   527.8 2455.42   530.3 2455.21   537.8 2454.58   545.3 2454.86   685.9 2468.27
   695.8 2469.35   705.7 2471.05   715.6 2473.96   725.4 2477.55   774.8 2497.08
   784.7 2500.62   873.6 2525.54   913.1 2537.48   942.7 2547.17   962.5 2554.34
   972.4 2558.32   992.1 2567.15  1021.7 2581.31  1031.6 2585.45  1130.4 2614.42
#Mann= 3 , 0 , 0
       0      .1       0   530.3    .045       0   545.3      .1       0
Bank Sta=530.3,545.3
XS Rating Curve= 0 ,0
Exp/Cntr=0.3,0.1

Type RM Length L Ch R = 1 ,8726.4  ,292.3,300,310.3
XS GIS Cut Line= 3
     2011324.427      373246.552     2011473.801      372689.105
     2011578.275      372157.721
#Sta/Elev= 30
       0 2604.82    39.8 2595.43    79.6 2584.11    99.5 2577.67   119.4 2569.83
   139.3 2563.11   218.9 2539.78   467.7 2471.32   487.6 2467.12   569.6 2453.67
   577.1 2452.91   584.6 2453.02   596.8 2454.18   626.4 2459.13     646 2463.39
   665.7 2468.92   695.3 2479.97   744.5 2501.91     774 2513.65     843 2535.42
   961.1  2576.9   980.8 2580.73   990.7 2584.24  1010.4 2593.42  1020.2 2596.93
  1069.4 2610.69  1089.1 2615.67    1099 2617.42  1108.8  2617.9  1118.7 2617.08
#Mann= 3 , 0 , 0
       0      .1       0   569.6    .045       0   584.6      .1       0
Bank Sta=569.6,584.6
XS Rating Curve= 0 ,0
Exp/Cntr=0.3,0.1

Type RM Length L Ch R = 1 ,8426.4  ,407.3,419.7,431.7
XS GIS Cut Line= 3
     2011402.706      373284.397     2011740.278       372818.42
     2012066.445      372387.037
#Sta/Elev= 30
       0 2594.16    79.4 2573.72   238.1  2528.8   337.3 2502.16   367.1 2492.59
   406.8  2478.3   436.5 2464.63   446.4 2460.96   456.4  2459.1     496  2456.5
   565.5 2450.12   567.9 2450.29   575.4 2450.84   582.9 2452.83   605.4 2461.84
   625.5 2468.61   655.5 2477.77   705.6 2491.02   725.6 2494.76   785.7 2502.69
   885.9  2522.1   905.9 2526.95   935.9  2535.9     986 2556.72     996 2559.59
    1006 2561.05  1036.1 2560.67  1066.1 2562.01  1096.2 2567.79  1116.2  2572.7
#Mann= 3 , 0 , 0
       0      .1       0   567.9    .045       0   582.9      .1       0
Bank Sta=567.9,582.9
XS Rating Curve= 0 ,0
Exp/Cntr=0.3,0.1

Type RM Length L Ch R = 1 ,8006.6  ,276.6,279.9,283.2
XS GIS Cut Line= 3
      2011475.63      373368.791     2012016.837      373141.885
      2012236.31      373003.007
#Sta/Elev= 30
       0 2586.73    19.9 2579.06    29.8  2575.7   139.2 2540.02     189 2524.23
   278.5 2497.24   308.3 2486.84     378 2460.09   387.9 2456.46   397.9 2453.35
   407.8 2451.64   417.8 2451.16   477.4 2451.86   507.3 2451.34   527.2  2450.1
   537.1 2448.86   556.3 2445.06     567 2444.57   571.3 2445.42   576.9 2446.52
   596.8 2453.44   606.8 2455.87   686.7 2468.49   696.7  2470.5   716.7 2475.71
   756.7 2485.23   776.6 2491.37   796.6 2498.42   816.6 2506.36   846.6 2519.46
#Mann= 3 , 0 , 0
       0      .1       0   556.3    .045       0   571.3      .1       0
Bank Sta=556.3,571.3
XS Rating Curve= 0 ,0
Exp/Cntr=0.3,0.1

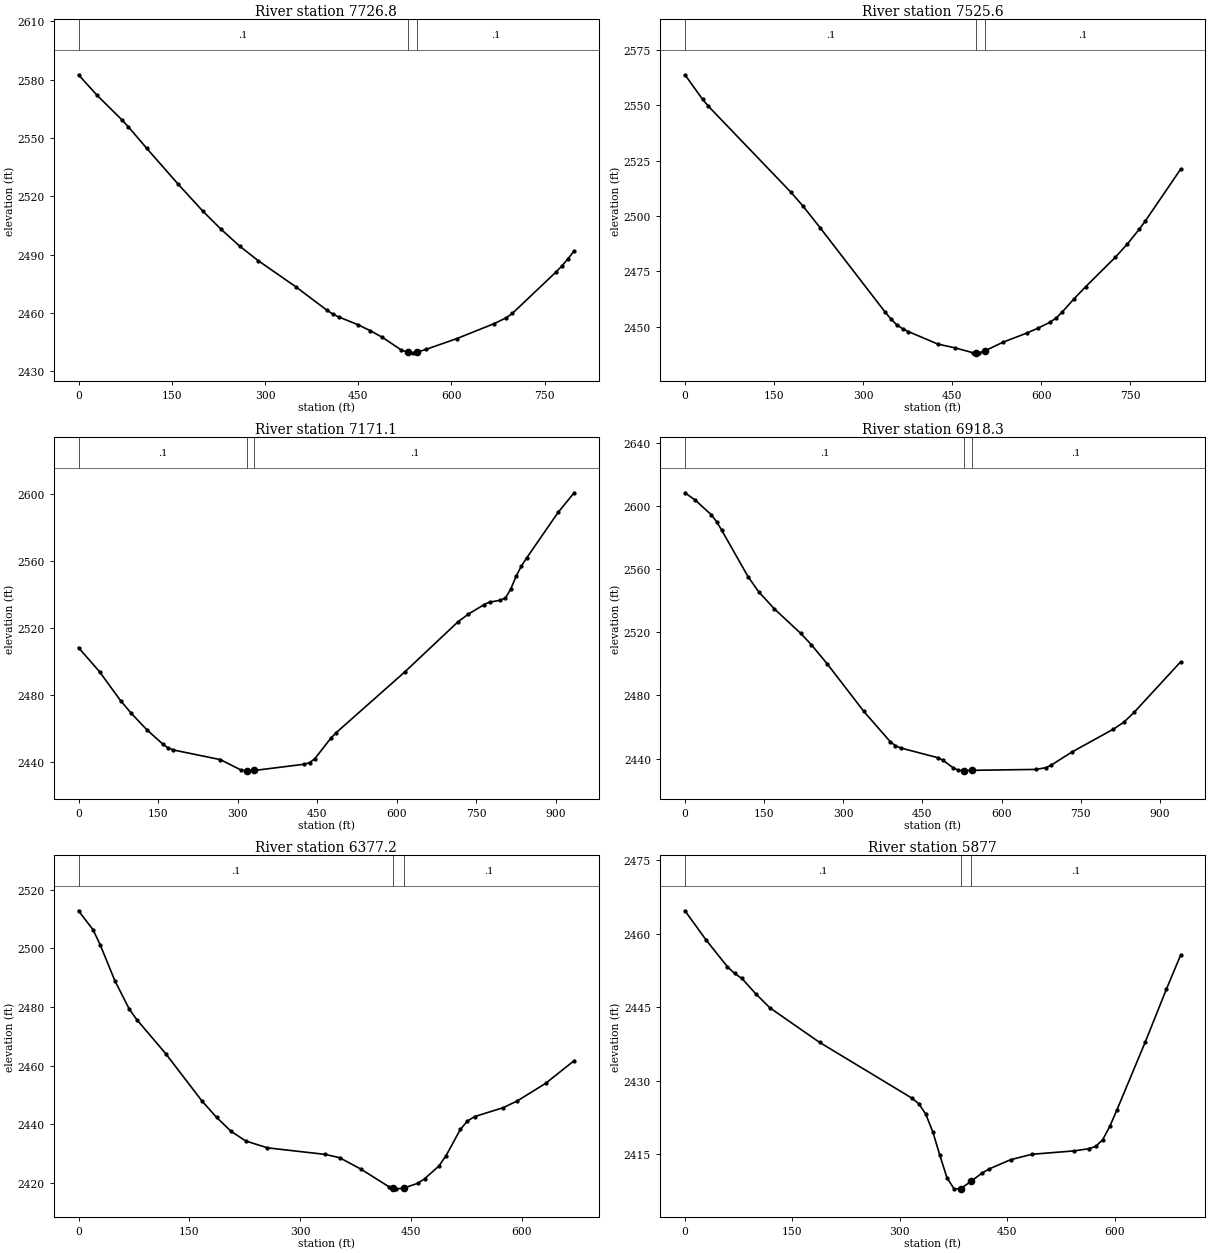
Type RM Length L Ch R = 1 ,7726.8  ,209.2,201.1,193.1
XS GIS Cut Line= 3
     2011538.248       373543.33      2012148.36      373392.783
     2012300.273      373318.826
#Sta/Elev= 30
       0  2582.5    29.9 2571.95    69.8 2559.34    79.8 2555.91   109.7 2544.71
   159.6 2526.54   199.5 2512.57   229.4 2503.07   259.3 2494.42   289.3  2486.9
   349.1 2473.64     399 2461.62     409 2459.52   418.9 2457.98   448.9 2454.12
   468.8 2451.03   488.8 2447.56   518.7 2441.15   529.4 2439.78   538.6 2439.57
   544.4 2439.94   558.6 2441.29   608.5 2446.88   668.2 2454.52     688 2457.57
     698 2459.85   767.6 2480.93   777.5  2484.2   787.4 2487.89   797.4    2492
#Mann= 3 , 0 , 0
       0      .1       0   529.4    .045       0   544.4      .1       0
Bank Sta=529.4,544.4
XS Rating Curve= 0 ,0
Exp/Cntr=0.3,0.1

Type RM Length L Ch R = 1 ,7525.6  ,364.9,354.4,343.7
XS GIS Cut Line= 3
     2011684.626      373756.575     2012116.378      373610.658
       2012428.2      373394.782
#Sta/Elev= 30
       0 2563.77    29.7 2552.67    39.6 2549.53   178.3  2510.8   198.2 2504.71
   227.9 2494.66   336.8 2456.79   346.8 2453.58   356.7 2450.96   366.6 2449.14
   376.5 2447.85     426 2442.22   455.7 2440.47   485.7 2438.27   489.8 2438.28
   495.7  2438.3   504.8  2439.1   535.6 2443.05   575.5 2447.15   595.5 2449.51
   615.4 2452.16   625.4 2454.02   635.4 2456.66   655.4 2462.63   675.3 2468.19
   725.2 2481.47   745.2 2487.37   765.1 2494.01   775.1 2497.61     835 2521.18
#Mann= 3 , 0 , 0
       0      .1       0   489.8    .045       0   504.8      .1       0
Bank Sta=489.8,504.8
XS Rating Curve= 0 ,0
Exp/Cntr=0.3,0.1

Type RM Length L Ch R = 1 ,7171.1  ,260.5,252.8,245.3
XS GIS Cut Line= 3
     2012205.661       374148.35     2012416.206      373777.896
     2012682.536      373344.483
#Sta/Elev= 30
       0  2508.4    39.6 2494.05    79.3 2476.73    99.1  2469.3   128.8 2459.34
   158.6 2450.85   168.5 2448.58   178.4 2447.27   267.6 2441.46   307.2 2435.14
   316.9 2434.76   331.9 2434.99   426.1 2438.73   436.1 2439.71     446 2442.12
     476 2454.32     486 2457.58   615.6 2493.96   715.4 2523.77   735.3 2528.47
   765.2 2534.17   775.2 2535.63   795.2  2536.7   805.1 2538.07   815.1 2543.31
   825.1 2550.95   835.1  2557.1     845 2561.93   904.9 2589.43   934.8 2600.99
#Mann= 3 , 0 , 0
       0      .1       0   316.9    .045       0   331.9      .1       0
Bank Sta=316.9,331.9
XS Rating Curve= 0 ,0
Exp/Cntr=0.3,0.1

Type RM Length L Ch R = 1 ,6918.3  ,526.9,540.6,554.2
XS GIS Cut Line= 3
     2012376.229      374500.148     2012565.454       374049.74
     2012637.413      373604.662
#Sta/Elev= 30
       0 2608.47    19.9  2603.7    49.8 2594.56    59.8 2590.22    69.8 2584.64
   119.6 2555.28   139.6 2545.74   169.5 2534.88   219.4 2519.34   239.3 2512.26
   269.2 2500.21     339  2469.9   388.8 2450.81   398.8  2448.2   408.8 2446.74
   478.6 2440.62   488.5 2439.02   508.1 2434.23     518 2432.64   527.8 2432.24
   528.7 2432.26   543.7 2432.56     665 2433.14   684.6 2434.27   694.4 2435.92
   733.6 2444.22     812 2458.66   831.6 2463.02   851.2 2469.28   939.4 2501.33
#Mann= 3 , 0 , 0
       0      .1       0   528.7    .045       0   543.7      .1       0
Bank Sta=528.7,543.7
XS Rating Curve= 0 ,0
Exp/Cntr=0.3,0.1

Type RM Length L Ch R = 1 ,6377.2  ,511.4,500.3,489.2
XS GIS Cut Line= 4
     2012810.647      374468.167     2012938.574      374180.332
     2013065.343      374048.526     2013087.821      373876.506
#Sta/Elev= 30
       0 2512.83    19.7 2506.35    29.5 2501.14    49.2 2488.98    68.9 2479.21
    78.8 2475.72   118.1 2464.07   167.3 2447.89     187 2442.32   206.7 2437.56
   226.4 2434.28   255.9 2431.93   334.2 2429.69   353.5 2428.58   382.4 2424.68
   420.9 2418.58   425.6 2418.27   430.5 2417.94   440.6 2418.21   459.4 2419.82
     469 2421.43   488.2 2425.75   497.9 2429.31   517.1 2438.19   526.8  2441.1
   536.4 2442.59     575 2445.62   594.2 2447.93   632.8 2453.96   671.3 2461.69
#Mann= 3 , 0 , 0
       0      .1       0   425.6    .045       0   440.6      .1       0
Bank Sta=425.6,440.6
XS Rating Curve= 0 ,0
Exp/Cntr=0.3,0.1

Type RM Length L Ch R = 1 ,5877    ,451,450.8,450.5
XS GIS Cut Line= 2
      2013351.67      374692.038      2013538.23      374025.754
#Sta/Elev= 30
       0  2464.7    29.6 2458.71    59.3 2453.28    69.2 2451.92    79.1 2450.95
    98.8 2447.76   118.6 2444.89   187.8 2437.86   316.3 2426.52   326.2 2425.37
   336.1 2423.22     346 2419.58   355.8 2414.79   365.7 2410.25   375.6 2407.97
   384.8 2407.98   399.8 2409.57   415.2 2411.24     425 2412.05   454.7 2413.92
   484.3 2415.02   543.6 2415.72   563.4 2416.15   573.3 2416.62   583.2 2418.02
   593.1 2420.74     603 2424.08   642.5 2437.92   672.1 2448.73   691.9 2455.66
#Mann= 3 , 0 , 0
       0      .1       0   384.8    .045       0   399.8      .1       0
Bank Sta=384.8,399.8
XS Rating Curve= 0 ,0
Exp/Cntr=0.3,0.1

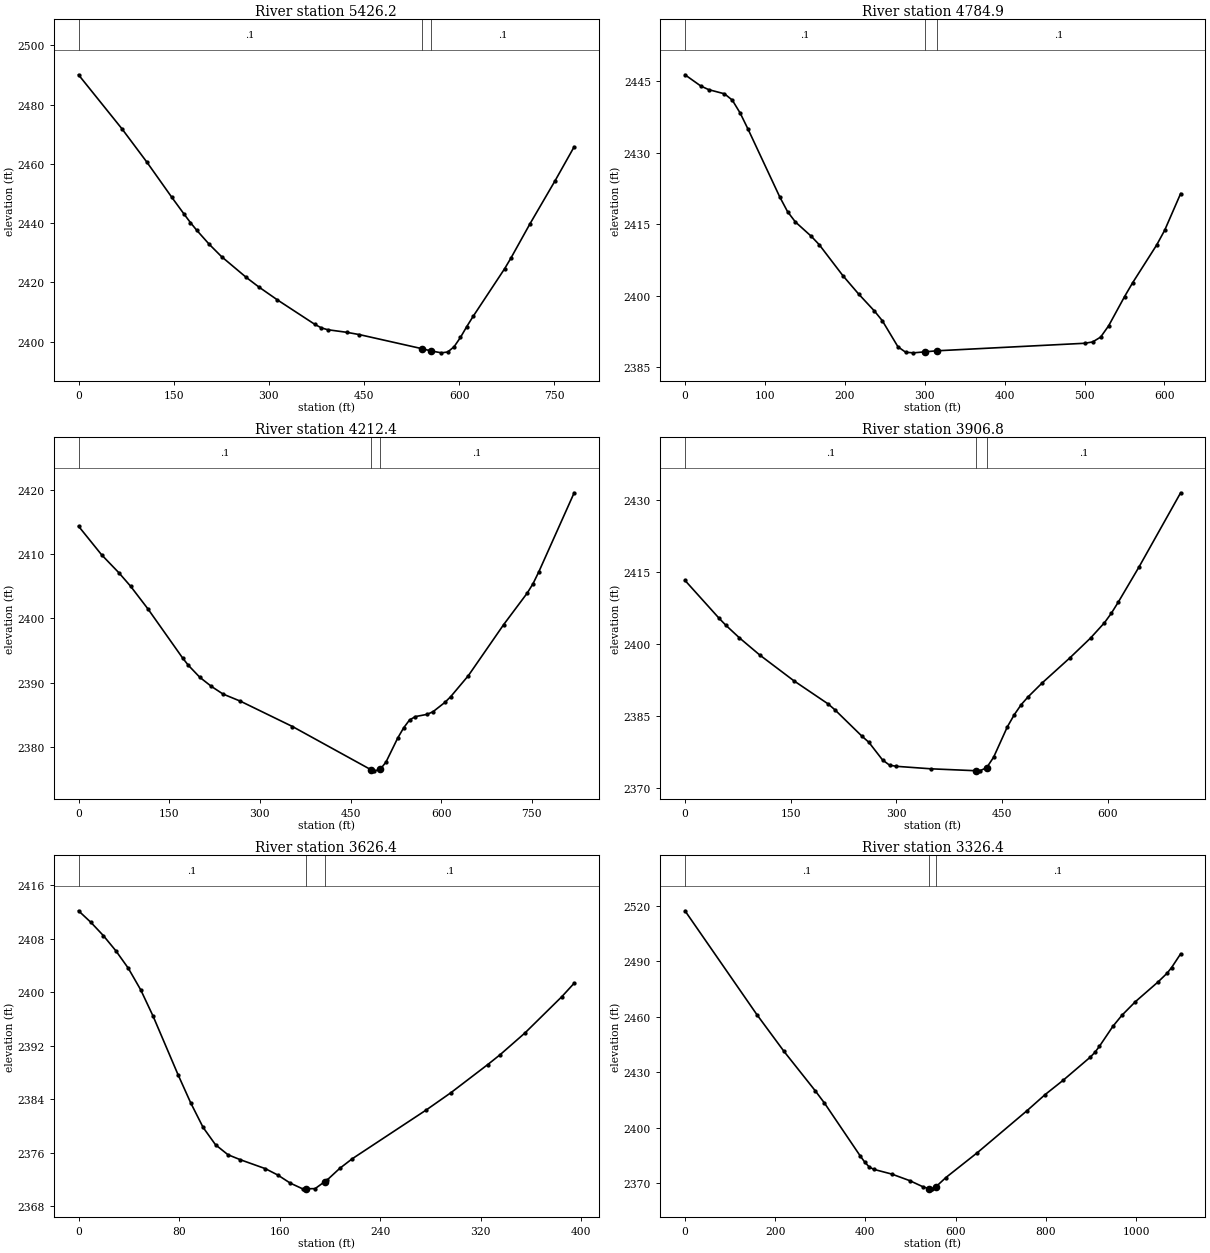
Type RM Length L Ch R = 1 ,5426.2  ,645.8,641.1,636.7
XS GIS Cut Line= 3
     2013702.802      374838.177     2013853.231      374529.956
     2013966.651      374106.596
#Sta/Elev= 30
       0 2490.07    68.6 2471.81   107.8 2460.59     147 2448.75   166.6 2443.01
   176.4 2440.21   186.2 2437.66   205.8 2432.94   225.4 2428.73   264.6 2421.68
   284.2 2418.49   313.6 2414.11   372.8 2405.83   382.8 2404.69   392.8 2404.06
   422.7 2403.19   442.6 2402.42     541 2397.68     556 2396.89   572.1 2396.26
     582 2396.55     592 2398.31     602 2401.44   611.9 2405.08   621.9 2408.52
   671.7 2424.65   681.6 2428.23   711.5 2439.74   751.4 2454.39   781.3 2465.78
#Mann= 3 , 0 , 0
       0      .1       0     541    .045       0     556      .1       0
Bank Sta=541,556
XS Rating Curve= 0 ,0
Exp/Cntr=0.3,0.1

Type RM Length L Ch R = 1 ,4784.9  ,550.3,572.7,594.8
XS GIS Cut Line= 4
     2014313.185      374925.913     2014428.773      374696.673
     2014448.335      374454.107      2014415.08      374338.693
#Sta/Elev= 30
       0 2446.39    19.8 2444.03    29.6 2443.27    49.4 2442.39    59.2 2441.07
    69.1 2438.33      79 2434.93   118.5 2420.75   128.4 2417.61   138.2 2415.45
     158 2412.45   167.9  2410.7   197.5 2404.19   217.2 2400.33     237 2396.75
   246.9 2394.71   266.5 2389.22   276.2 2388.07   285.9 2387.95   300.3 2388.16
   315.3 2388.38   500.1 2389.96   510.1 2390.24   520.1 2391.26   530.1 2393.63
   550.1 2399.79   560.1 2402.67   590.2 2410.61   600.2  2413.7   620.2 2421.42
#Mann= 3 , 0 , 0
       0      .1       0   300.3    .045       0   315.3      .1       0
Bank Sta=300.3,315.3
XS Rating Curve= 0 ,0
Exp/Cntr=0.3,0.1

Type RM Length L Ch R = 1 ,4212.4  ,306.7,305.3,304
XS GIS Cut Line= 5
      2014563.75       375005.75     2014706.551      374851.211
     2014857.176      374718.191     2014949.117      374663.418
     2015199.507      374495.187
#Sta/Elev= 30
       0 2414.36    38.3 2409.89      67 2407.08    86.1 2405.01   114.8 2401.48
   172.2 2393.83   181.7 2392.69   200.8 2390.81     220 2389.39   239.1 2388.21
   267.8  2387.1     354 2383.15   483.9 2376.42   489.2 2376.25   498.9 2376.46
   508.7 2377.62   528.1 2381.36   537.8 2382.93   547.6 2384.17   557.3  2384.7
   576.8 2385.05   586.5 2385.46     606  2386.9   615.7  2387.8   644.9 2391.07
   703.3 2399.02   742.2 2403.92   751.9 2405.39   761.7 2407.29     820 2419.56
#Mann= 3 , 0 , 0
       0      .1       0   483.9    .045       0   498.9      .1       0
Bank Sta=483.9,498.9
XS Rating Curve= 0 ,0
Exp/Cntr=0.3,0.1

Type RM Length L Ch R = 1 ,3906.8  ,280.8,280.3,279.6
XS GIS Cut Line= 3
     2014841.527      375195.499     2014999.977      374988.144
      2015368.28      374742.436
#Sta/Elev= 30
       0 2413.26    48.3 2405.39      58 2403.92    77.3 2401.29   106.3  2397.7
   154.6 2392.35     203 2387.55   212.6 2386.34   251.3  2380.8     261 2379.55
   280.6 2375.84   290.5 2374.77   300.3 2374.53   349.5 2374.01   413.2 2373.61
   418.4 2373.59   428.2 2374.23   438.1  2376.4   457.7 2382.76   467.6  2385.3
   477.4 2387.39   487.2 2389.01   506.9 2391.87   546.3  2397.1   575.8 2401.25
   595.5 2404.43   605.3 2406.41   615.2 2408.74   644.7 2416.08   703.7 2431.51
#Mann= 3 , 0 , 0
       0      .1       0   413.2    .045       0   428.2      .1       0
Bank Sta=413.2,428.2
XS Rating Curve= 0 ,0
Exp/Cntr=0.3,0.1

Type RM Length L Ch R = 1 ,3626.4  ,301.3,299.9,299.3
XS GIS Cut Line= 3
     2015070.018      375265.931      2015224.15      375157.908
     2015391.833      375038.062
#Sta/Elev= 30
       0 2412.19     9.9 2410.45    19.8 2408.47    29.7 2406.21    39.6  2403.6
    49.5 2400.36    59.4  2396.4    79.2 2387.67    89.2 2383.49    99.1  2379.8
     109  2377.2   118.9 2375.71   128.8 2374.96   148.6 2373.63   158.5 2372.68
   168.4 2371.47   178.3 2370.61   180.7 2370.62   188.2 2370.64   195.7 2371.66
     198 2371.97   207.8 2373.67   217.7  2375.1   276.6  2382.4   296.2 2384.98
   325.6  2389.2   335.4 2390.67   355.1 2393.91   384.5 2399.35   394.3 2401.36
#Mann= 3 , 0 , 0
       0      .1       0   180.7    .045       0   195.7      .1       0
Bank Sta=180.7,195.7
XS Rating Curve= 0 ,0
Exp/Cntr=0.3,0.1

Type RM Length L Ch R = 1 ,3326.4  ,304.5,300.1,295.4
XS GIS Cut Line= 3
        2015015.      375693.245     2015442.272      375349.542
     2015882.651      375019.357
#Sta/Elev= 30
       0  2517.4   159.5 2461.16   219.3 2441.36   289.1 2419.87   309.1 2413.36
   388.8 2384.59   398.8 2381.26   408.8 2378.64   418.7 2377.43   458.6 2374.87
   498.5  2371.3   528.4 2367.91   540.9 2366.94   548.4 2366.89   555.9 2367.92
   578.4    2373   648.4 2386.52   758.5 2409.25   798.5 2417.93   838.6  2425.7
   898.6  2438.2   908.6 2440.73   918.6 2443.98   948.7 2454.88   968.7 2460.85
   998.7 2468.24  1048.7 2478.87  1068.8 2483.61  1078.8 2486.68  1098.8 2494.09
#Mann= 3 , 0 , 0
       0      .1       0   540.9    .045       0   555.9      .1       0
Bank Sta=540.9,555.9
XS Rating Curve= 0 ,0
Exp/Cntr=0.3,0.1

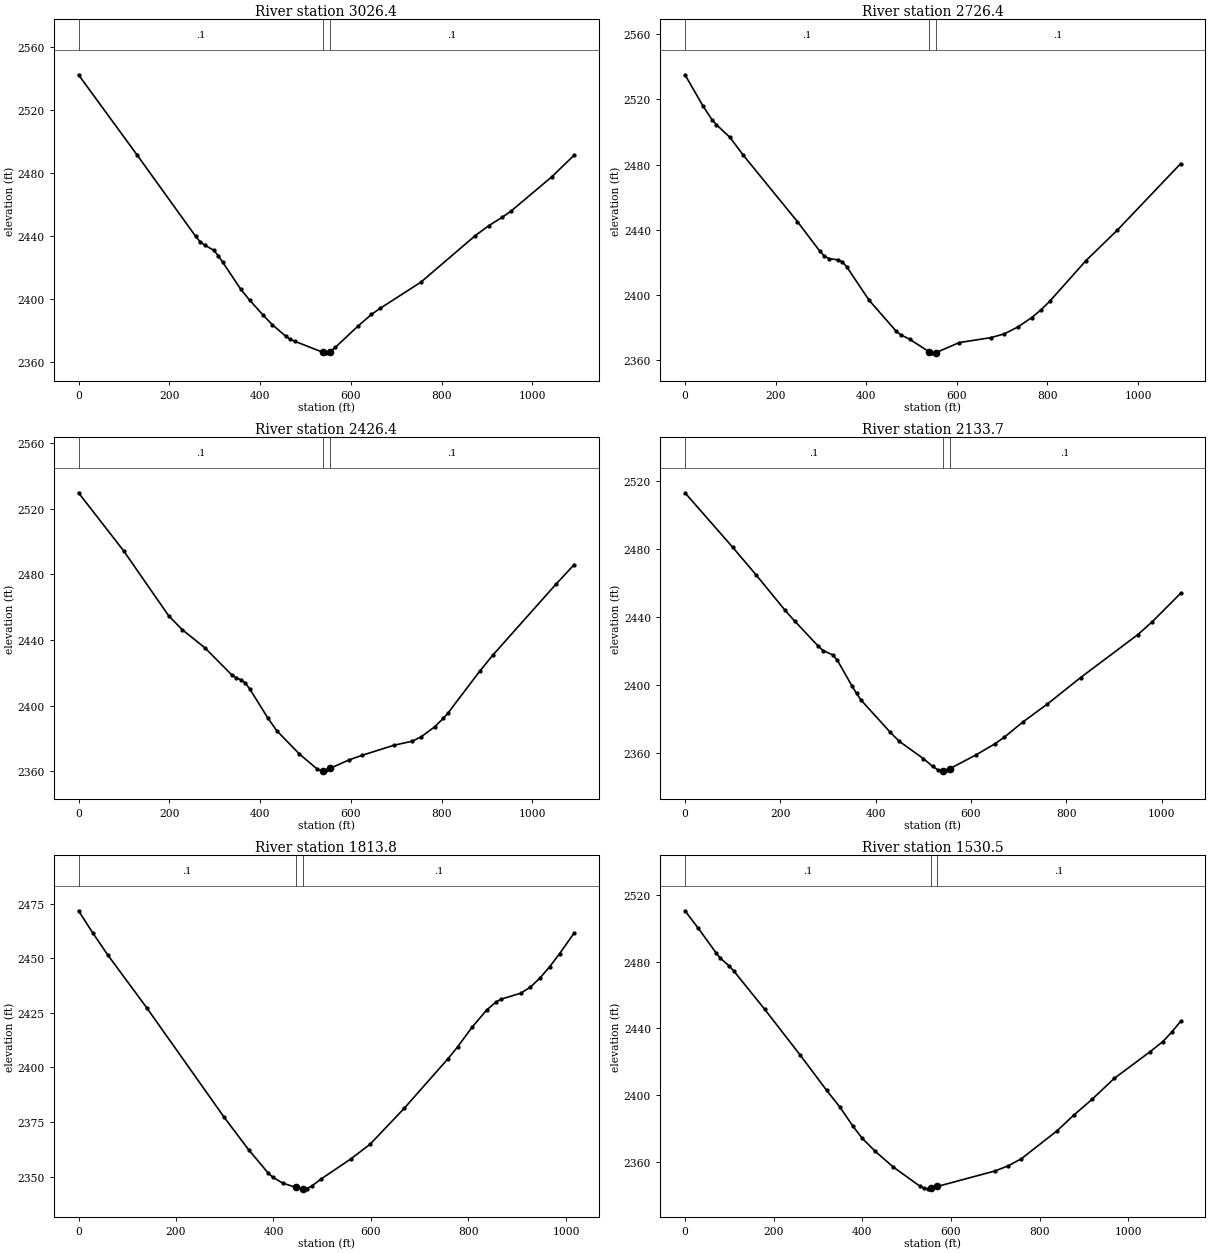
Type RM Length L Ch R = 1 ,3026.4  ,294.4,300,304
XS GIS Cut Line= 3
     2015311.887      375966.407     2015663.142      375548.189
      2016023.26      375137.822
#Sta/Elev= 30
       0 2542.34   129.1 2491.42   258.2 2439.71   268.1 2436.31     278 2434.23
   297.9 2430.93   307.8 2427.48   317.8 2423.33   357.5 2406.15   377.3 2399.18
   407.1 2389.63     427 2383.67   456.8 2376.32   466.7 2374.39   476.6 2373.13
   538.7 2366.11   546.2  2365.8   553.7 2366.65   556.1 2366.92     566 2369.31
   615.6 2382.74   645.4 2390.17   665.3 2394.17   754.6 2410.72   873.7  2440.1
   903.5 2446.46   933.3 2451.82   953.2 2455.84  1042.5 2477.48  1092.1  2491.3
#Mann= 3 , 0 , 0
       0      .1       0   538.7    .045       0   553.7      .1       0
Bank Sta=538.7,553.7
XS Rating Curve= 0 ,0
Exp/Cntr=0.3,0.1

Type RM Length L Ch R = 1 ,2726.4  ,305.5,300,295.5
XS GIS Cut Line= 3
     2015414.879      376091.352     2015858.324      375773.584
        2016287.      375431.504
#Sta/Elev= 30
       0 2535.05    39.7 2515.96    59.5  2507.6    69.4 2504.44    99.2  2496.7
     129 2485.66     248  2445.1   297.6 2426.95   307.5 2423.96   317.4 2422.39
   337.2 2421.63   347.2 2420.43   357.1 2417.31   406.7 2396.74   466.2 2377.86
   476.1  2375.7     496 2372.92     538 2365.41   545.6 2364.61     553 2364.61
   605.4  2370.9   675.2 2373.94   705.1 2376.26     735 2380.52   764.9 2386.14
   784.9 2390.73   804.8 2396.13   884.6 2421.01   954.4 2439.87    1094 2480.57
#Mann= 3 , 0 , 0
       0      .1       0     538    .045       0     553      .1       0
Bank Sta=538,553
XS Rating Curve= 0 ,0
Exp/Cntr=0.3,0.1

Type RM Length L Ch R = 1 ,2426.4  ,290.6,292.7,295
XS GIS Cut Line= 3
     2015725.122      376390.906     2016078.992      375975.108
     2016429.608      375556.531
#Sta/Elev= 30
       0 2529.61    99.3 2494.31   198.5 2454.74   228.3 2446.29     278  2435.3
   337.5 2418.74   347.4 2416.96   357.4 2415.76   367.3  2413.8   377.2 2410.15
   416.9 2392.54   436.8 2384.68   486.4 2370.58   526.1 2361.28   536.1 2360.26
   538.5 2360.37     546 2360.73   553.5 2361.71   595.6 2366.86   625.4 2369.78
   694.9 2375.84   734.6 2378.27   754.5 2380.88   784.3 2386.99   804.1 2392.31
     814 2395.45   883.5 2420.79   913.3  2430.9  1052.3 2474.04    1092 2485.85
#Mann= 3 , 0 , 0
       0      .1       0   538.5    .045       0   553.5      .1       0
Bank Sta=538.5,553.5
XS Rating Curve= 0 ,0
Exp/Cntr=0.3,0.1

Type RM Length L Ch R = 1 ,2133.7  ,320.3,319.7,319.2
XS GIS Cut Line= 2
      2015910.76      376545.361     2016655.775      375819.614
#Sta/Elev= 30
       0 2512.85     100  2480.9     150 2464.41     210 2443.86     230  2437.6
     280 2422.71     290  2420.2     310 2417.66     320 2414.42     350 2399.66
     360 2395.03     370 2390.99     430 2372.47     450 2366.87     500 2356.84
     520 2352.18     530 2350.31     540 2349.61   540.8 2349.65     550 2350.05
   555.8 2350.88     610 2358.87     650 2365.41     670 2369.35     710 2378.48
     760 2388.72   830.1 2404.35   950.1 2429.54   980.1 2437.02  1040.1 2453.83
#Mann= 3 , 0 , 0
       0      .1       0   540.8    .045       0   555.8      .1       0
Bank Sta=540.8,555.8
XS Rating Curve= 0 ,0
Exp/Cntr=0.3,0.1

Type RM Length L Ch R = 1 ,1813.8  ,293.3,283.3,273.3
XS GIS Cut Line= 2
     2016165.389      376744.417     2016883.379       376024.47
#Sta/Elev= 30
       0 2471.72    29.9 2461.37    59.8 2451.56   139.6  2427.4     299 2377.09
   348.9 2362.32   388.8  2351.7   398.7 2349.68   418.7 2347.02   446.2 2345.03
   458.6 2344.38   461.2 2344.41   468.5  2344.5   478.5 2345.67   498.4    2349
   558.2    2358   598.1  2364.8   667.9 2381.19   757.6 2403.87   777.5 2409.33
   807.4 2418.42   837.3 2426.27   857.3 2430.06   867.2 2431.26   907.1 2433.96
   927.1 2436.76     947 2441.02   966.9  2446.2   986.9 2452.07  1016.8 2461.57
#Mann= 3 , 0 , 0
       0      .1       0   446.2    .045       0   461.2      .1       0
Bank Sta=446.2,461.2
XS Rating Curve= 0 ,0
Exp/Cntr=0.3,0.1

Type RM Length L Ch R = 1 ,1530.5  ,405.2,414,422.7
XS GIS Cut Line= 2
     2016505.377      377133.824     2016864.555      376074.928
#Sta/Elev= 30
       0 2510.41      30 2499.95    69.9 2485.29    79.9 2482.01    99.8 2477.32
   109.8 2474.47   179.7 2451.45   259.6 2424.12   319.5  2402.9   349.4 2392.87
   379.4 2381.25   399.3 2374.31   429.3 2366.35   469.2  2357.1   529.1 2345.66
   539.1 2344.22   549.1 2343.89   554.2 2344.16   569.2  2345.3   698.8 2354.55
   728.8 2357.62   758.8 2361.89   838.6 2378.47   878.6 2388.37   918.5 2397.51
   968.4 2410.03  1048.3 2425.81  1078.2 2432.12  1098.2 2437.78  1118.2 2444.24
#Mann= 3 , 0 , 0
       0      .1       0   554.2    .045       0   569.2      .1       0
Bank Sta=554.2,569.2
XS Rating Curve= 0 ,0
Exp/Cntr=0.3,0.1

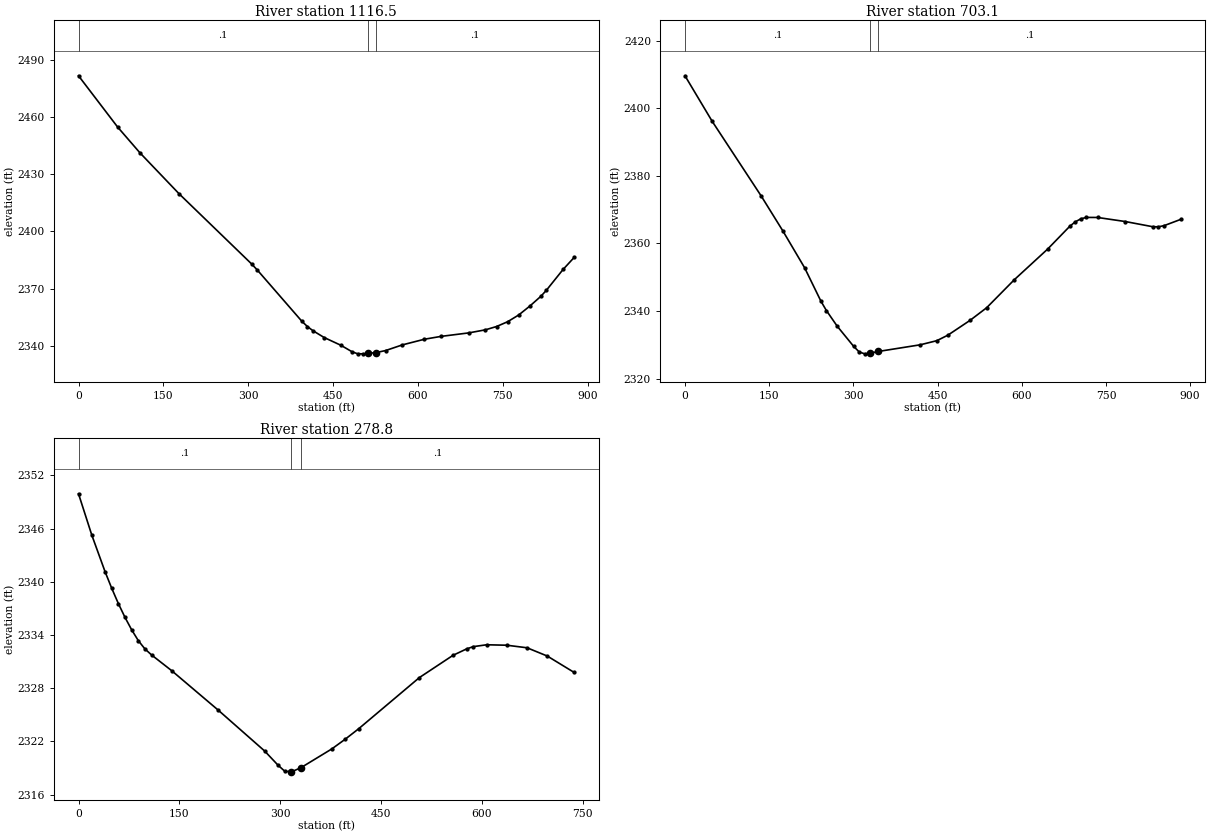
Type RM Length L Ch R = 1 ,1116.5  ,421.7,413.4,405
XS GIS Cut Line= 3
     2016693.087      377141.522     2017071.302      376725.304
     2017196.798      376437.926
#Sta/Elev= 30
       0 2481.52    69.1 2454.66   108.5 2441.16   177.6 2419.72   305.9 2382.91
   315.7 2379.82   394.7 2352.87   404.5 2350.11   414.4  2347.9   434.1 2344.35
   463.7 2340.28   483.5 2336.87   493.3 2335.83   503.2 2335.79   511.1    2336
   526.1 2336.46   542.7 2337.51   572.2 2340.47   611.4 2343.45   640.8 2344.94
   689.8 2346.77   719.2 2348.38   738.8 2350.11   758.4 2352.62     778 2356.16
   797.6 2360.81   817.2 2365.96     827 2369.14   856.4 2380.01     876 2386.32
#Mann= 3 , 0 , 0
       0      .1       0   511.1    .045       0   526.1      .1       0
Bank Sta=511.1,526.1
XS Rating Curve= 0 ,0
Exp/Cntr=0.3,0.1

Type RM Length L Ch R = 1 ,703.1   ,414.9,424.3,433.7
XS GIS Cut Line= 3
      2017151.49      377216.146     2017367.367      377021.591
     2017574.851      376466.755
#Sta/Elev= 30
       0 2409.59    48.4 2396.13   135.6 2374.06   174.4 2363.67   213.1 2352.78
   242.2 2342.88   251.9 2340.12   271.2 2335.48   300.5 2329.51   310.4 2327.86
   320.2  2327.3   329.3 2327.48   344.3    2328     419 2329.97   448.6 2331.19
   468.3 2332.82   507.8  2337.2   537.4 2340.94   586.8 2349.25     646 2358.29
   685.5 2365.05   695.4 2366.38   705.3 2367.26   715.1 2367.67   734.9 2367.66
   784.2 2366.46   833.6 2364.91   843.5  2364.9   853.4 2365.23     883 2367.08
#Mann= 3 , 0 , 0
       0      .1       0   329.3    .045       0   344.3      .1       0
Bank Sta=329.3,344.3
XS Rating Curve= 0 ,0
Exp/Cntr=0.3,0.1

Type RM Length L Ch R = 1 ,278.8   ,257.4,252.4,248
XS GIS Cut Line= 3
     2017439.325      377298.765     2017713.835      377216.146
     2018027.624      376892.967
#Sta/Elev= 30
       0 2349.93    19.8 2345.26    39.5 2341.14    49.4 2339.27    59.3 2337.54
    69.2 2335.98    79.1 2334.58      89 2333.36    98.8 2332.43   108.7 2331.75
   138.4 2329.99   207.6 2325.54   276.8 2320.92   296.7 2319.32   306.7 2318.64
   315.6 2318.58   316.7 2318.57   330.6 2319.03   376.8 2321.16   396.8 2322.26
   416.8 2323.44   506.9  2329.2   556.9 2331.71     577 2332.43     587 2332.69
     607  2332.9     637 2332.85   667.1 2332.56   697.1 2331.63   737.1 2329.78
#Mann= 3 , 0 , 0
       0      .1       0   315.6    .045       0   330.6      .1       0
Bank Sta=315.6,330.6
XS Rating Curve= 0 ,0
Exp/Cntr=0.3,0.1