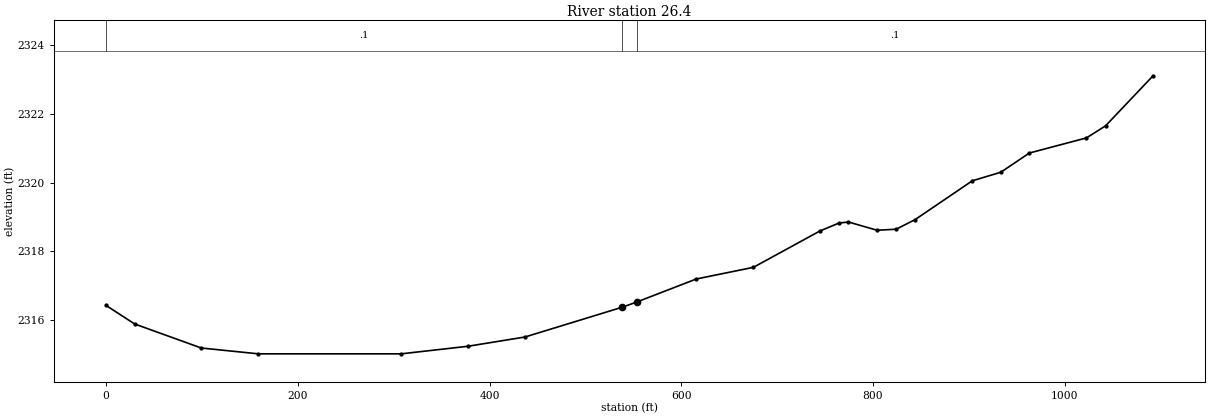
HEC-RAS study LaurelCrk5.prj: LaurelCrk5

--- LaurelCrk5.g01 (geometry) --- (continued)

Type RM Length L Ch R = 1 ,26.4    ,26.6,26.4,25.6
XS GIS Cut Line= 3
     2017643.374      377823.468     2017926.753      377356.641
     2018224.337      376898.829
#Sta/Elev= 23
       0 2316.42    29.8 2315.88    99.3 2315.18   158.9 2315.01   307.8 2315.01
   377.3 2315.23   436.9  2315.5   538.6 2316.37   553.6 2316.52   615.6 2317.19
   675.2 2317.53   744.7 2318.59   764.5 2318.82   774.4 2318.85   804.2 2318.61
   824.1 2318.64   843.9 2318.92   903.5 2320.05   933.3  2320.3   963.1 2320.86
  1022.6  2321.3  1042.5 2321.65  1092.1 2323.11
#Mann= 3 , 0 , 0
       0      .1       0   538.6    .045       0   553.6      .1       0
Bank Sta=538.6,553.6
XS Rating Curve= 0 ,0
Exp/Cntr=0.3,0.1

Chan Stop Cuts=-1
Use User Specified Reach Order=0
Composite Channel Slope=5